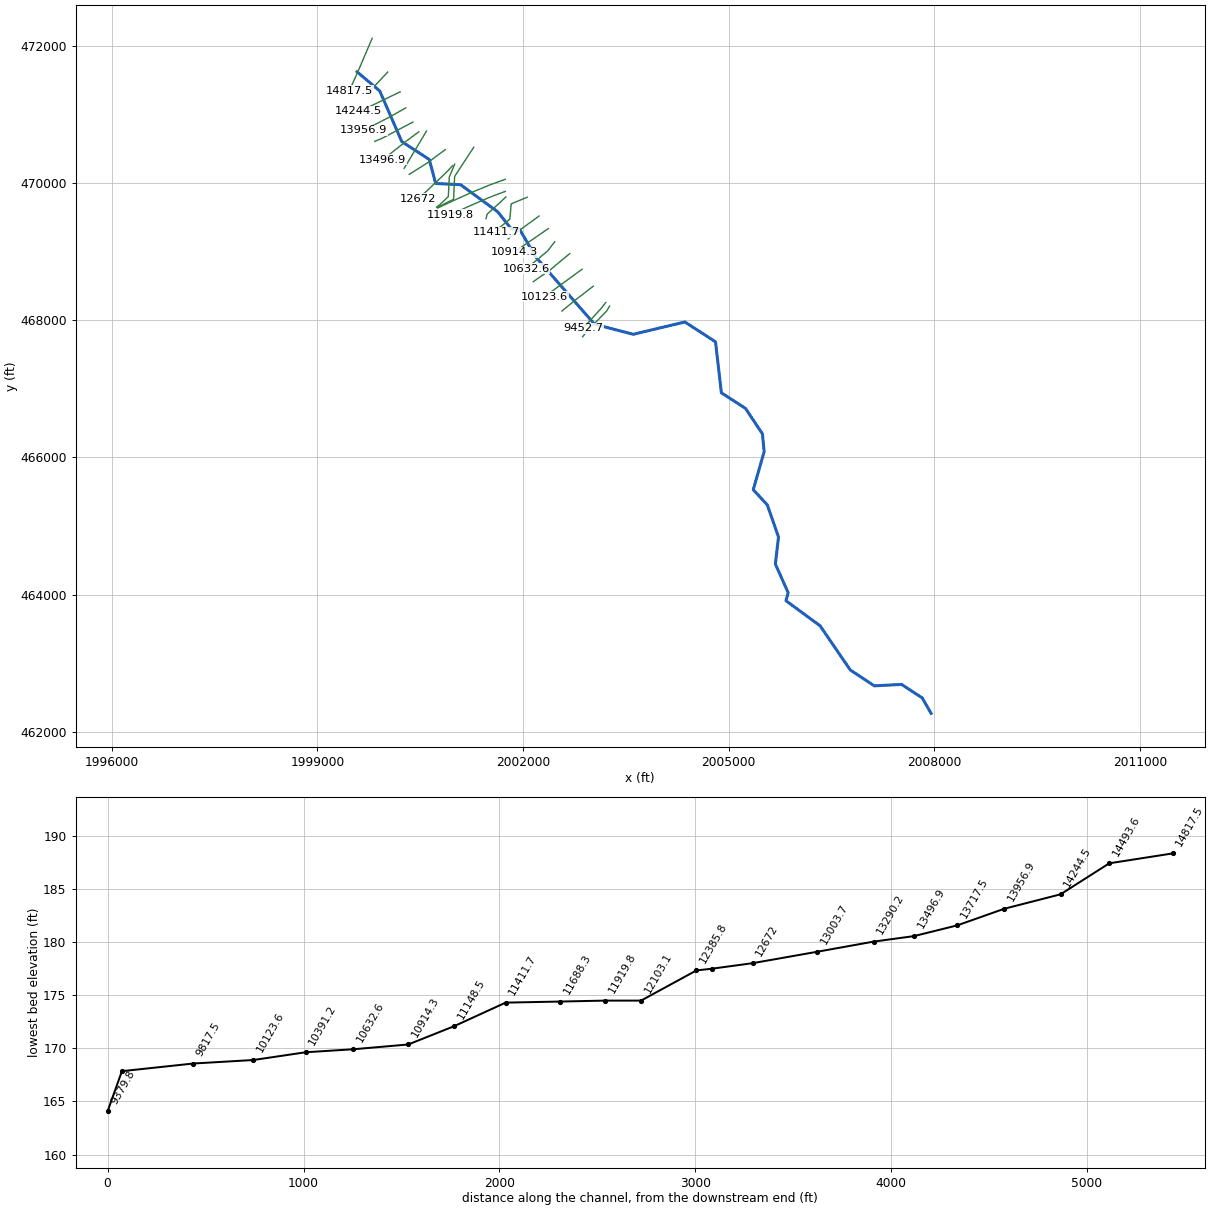
--- BeaverCTA.PRJ (project) ---

Proj Title=BeaverCTA
Current Plan=p01
Default Exp/Contr=0,0
English Units
Geom File=g01
Flow File=f01
Flow File=f02
Plan File=p01
Plan File=p02
BEGIN DESCRIPTION:
END DESCRIPTION:
DSS Export Rating Curves= 0
DSS Export Rating Curve Sorted= 0
DSS Export Volume Flow Curves= 0
DXF OffsetX= 0
DXF OffsetY= 0
DXF ScaleX= 0
DXF ScaleY= 0

--- BeaverCTA.P01 (plan) ---

Plan Title=Existing Conditions
Program Version=4.10
Short Identifier=Ex
Geom File=g01
Flow File=f01
Subcritical Flow
K Sum by GR=0
Std Step Tol=0.01
Critical Tol=0.01
Num of Std Step Trials=20
Max Error Tol=0.3
Flow Tol Ratio=0.001
Split Flow NTrial=30
Split Flow Tol=0.02
Split Flow Ratio=0.02
Log Output Level=0
Friction Slope Method=1
Unsteady Friction Slope Method=2
Unsteady Bridges Friction Slope Method=1
Parabolic Critical Depth
Global Vel Dist=0 , 0 , 0
Global Log Level=0
CheckData=True
Encroach Param=-1 ,10,10, 2
Encroach River=BeaverCTA
Encroach Reach=Main
Encroach Node=14817.5
       1  9905.5 10051.5
Encroach Node=14493.6
       1  9915.6 10015.3
Encroach Node=14244.5
       1  9949.4 10081.4
Encroach Node=13956.9
       1  9934.3 10089.5
Encroach Node=13717.5
       1  9937.7 10082.5
Encroach Node=13496.9
       1  9924.6 10076.4
Encroach Node=13290.2
       1  9906.9 10056.4
Encroach Node=13003.7
       1  9927.3 10105.4
Encroach Node=12672
       1  9907.1 10053.6
Encroach Node=12463.9
       1  9938.1 10066.1
Encroach Node=12385.8
       1  9939.0 10078.2
Encroach Node=12103.1
       1  9969.5 10021.5
Encroach Node=11919.8
       1  9970.9 10009.5
Encroach Node=11688.3
       1  9966.4 10053.1
Encroach Node=11411.7
       1  9983.6 10026.7
Encroach Node=11148.5
       1  9972.3 10058.5
Encroach Node=10914.3
       1    9960   10026
Encroach Node=10632.6
       1  9966.5 10015.2
Encroach Node=10391.2
       1  9917.8 10090.3
Encroach Node=10123.6
       1  9855.2 10146.3
Encroach Node=9817.5
       1  9850.6 10137.7
Encroach Node=9452.7
       1    9792 10083.3
Encroach Node=9379.8
       1  9765.6 10069.8
Encroach Node=9294.5
       1    9830   10038
Encroach Node=9175.7
       1  9929.8 10066.5
Encroach Node=8876.2
       1  9961.8 10110.9
Encroach Node=8576
       1  9896.3 10086.6
Encroach Node=8370.8
       1  9868.3 10073.6
Encroach Node=8274.6
       1  9875.1 10086.2
Encroach Node=8084.7
       1  9853.9 10062.8
Encroach Node=8031.6
       1  9913.3 10056.9
Encroach Node=7938.5
       1  9934.2 10046.6
Encroach Node=7841.3
       1    9950 10031.5
Encroach Node=7686.1
       1    9966 10042.7
Encroach Node=7559.4
       1  9903.6 10064.3
Encroach Node=7358.1
       1  9916.3 10083.2
Encroach Node=7144.5
       1  9942.6 10100.6
Encroach Node=6817.5
       1  9799.6 10203.9
Encroach Node=6317.5
       1  9828.2 10079.3
Encroach Node=6010.8
       1  9859.6 10140.6
Encroach Node=5684
       1  9824.8 10228.9
Encroach Node=5377.7
       1  9867.9 10144.2
Encroach Node=5030.5
       1  9834.7 10177.2
Encroach Node=4772.9
       1  9802.7 10140.9
Encroach Node=4645.7
       1  9825.5 10196.4
Encroach Node=4496.6
       1  9975.7 10029.3
Encroach Node=4386.5
       1  9976.7 10035.9
Encroach Node=4250.2
       1    9980 10043.3
Encroach Node=4095.7
       1  9979.8 10075.2
Encroach Node=3837.7
       1  9941.6 10063.6
Encroach Node=3529.5
       1  9957.4 10076.3
Encroach Node=3322.8
       1  9947.7 10066.7
Encroach Node=2817.5
       1  9948.3 10058.2
Encroach Node=2381.1
       1  9956.6   10064
Encroach Node=1996.7
       1  9964.3 10064.6
Encroach Node=1797.6
       1  9924.9 10026.1
Encroach Node=1317.5
       1  9968.8 10055.3
Encroach Node=1006.1
       1  9962.7 10093.8
Encroach Node=773.6
       1    9962 10082.2
Encroach Node=359.5
       1  9817.9   10015
Run HTab=0
Run UNet=0
Run PostProcess=0
UNET Theta=0
UNET Theta Warmup=0
UNET ZTol=0
UNET ZSATol=0
UNET MxIter=0
UNET MaxInSteps=0
UNET DtIC=0
UNET DtMin=0
UNET MaxCRTS=0
UNET WFStab=0
UNET SFStab=0
UNET WFX=1
UNET SFX=1
UNET DSS MLevel=1
UNET DZMax Abort=0
UNET Convert EG Bridges=0
UNET Use Existing IB Tables=0
UNET Froude Reduction=False
UNET Froude Limit=0
UNET Froude Power=0
Write IC File=0
Echo Input=False
Echo Output=False
Write Detailed=0

--- BeaverCTA.P02 (plan) ---

Plan Title=Future Conditions
Program Version=4.10
Short Identifier=Fut
Geom File=g01
Flow File=f02
Subcritical Flow
K Sum by GR= 0
Std Step Tol= 0.01
Critical Tol= 0.01
Num of Std Step Trials= 20
Max Error Tol= 0.3
Flow Tol Ratio= 0.001
Split Flow NTrial= 30
Split Flow Tol= 0.02
Split Flow Ratio= 0.02
Log Output Level= 0
Friction Slope Method= 1
Unsteady Friction Slope Method= 2
Unsteady Bridges Friction Slope Method= 1
Parabolic Critical Depth
Global Vel Dist= 0 , 0 , 0
Global Log Level= 0
CheckData=True
Encroach Param=-1 ,0,0, 0
Run HTab= 0
Run UNet= 0
Run PostProcess= 0
Run WQNet= 0
UNET Theta= 0
UNET Theta Warmup= 0
UNET ZTol= 0
UNET ZSATol= 0
UNET MxIter= 0
UNET MaxInSteps= 0
UNET DtIC= 0
UNET DtMin= 0
UNET MaxCRTS= 0
UNET WFStab= 0
UNET SFStab= 0
UNET WFX= 1
UNET SFX= 1
UNET DSS MLevel= 1
UNET DZMax Abort= 0
UNET Convert EG Bridges= 0
UNET Use Existing IB Tables= 0
UNET Froude Reduction=False
UNET Froude Limit= 0
UNET Froude Power= 0
UNET Time Slicing=0,0, 5
UNET Junction Losses=0
Write IC File= 0
Write IC File at Sim End=0
Echo Input=False
Echo Parameters=False
Echo Output=False
Write Detailed= 0
WQ AD Non Conservative
WQ ULTIMATE=-1
WQ Max Comp Step=1HOUR
WQ Output Interval=15MIN
WQ Output Selected Increments= 0
WQ Output face flow=0
WQ Output face velocity=0
WQ Output face area=0
WQ Output face dispersion=0
WQ Output cell volume=0
WQ Output cell surface area=0
WQ Output cell continuity=0
WQ Output cumulative cell continuity=0
WQ Output face conc=0
WQ Output face dconc_dx=0
WQ Output face courant=0
WQ Output face peclet=0
WQ Output face adv mass=0
WQ Output face disp mass=0
WQ Output cell mass=0
WQ Output cell source sink temp=0
WQ Output cell source sink nsm=0
WQ Output MaxMinRange=-1
WQ Daily Max Min Mean=-1
WQ Daily Range=0
WQ Daily Time=0
WQ Create Restart=0
WQ Fixed Restart=0
WQ System Summary=0
WQ Use Fixed Temperature=0
Sorting and Armoring Iterations= 10
XS Update Threshold= 0.02
Hydraulics Update Threshold= 0.02
Energy Slope Method= 1
Volume Change Method= 0
XS Weighting Method= 0
Number of US Weighted Cross Sections= 1
Number of DS Weighted Cross Sections= 1
Upstream XS Weight=0.25
Main XS Weight=0.5
Downstream XS Weight=0.25
Number of DS XS's Weighted with US Boundary= 1
Upstream Boundary Weight= 1
Weight of XSs Associated with US Boundary= 0
Number of US XS's Weighted with DS Boundary= 1
Downstream Boundary Weight= 0.5
Weight of XSs Associated with DS Boundary= 0.5
Sediment Output Level= 4
Mass or Volume Output= 0
Output Increment Type= 1
Profile and TS Output Increment= 10
XS Output Flag= 0
XS Output Increment= 10
Disregard all LS=0
Disregard all Conn=0
Disregard all Breaches=0
Disregard all Pumps=0

--- BeaverCTA.F01 (steady flow) ---

Flow Title=USGS Regression 10, 25, 50, 100, 500
Program Version=4.10
Number of Profiles= 6
Profile Names=P100yr,FWY,P10yr,P25yr,P50yr,P500yr
River Rch & RM=BeaverCTA,Main            ,14817.5
     820     820     468     616     722    1099
River Rch & RM=BeaverCTA,Main            ,12672
     911     911     524     686     804    1219
River Rch & RM=BeaverCTA,Main            ,11148.5
     998     998     578     753     881    1331
River Rch & RM=BeaverCTA,Main            ,8031.6
    1109    1109     647     839     981    1476
River Rch & RM=BeaverCTA,Main            ,4645.7
    1218    1218     716     923    1078    1616
Boundary for River Rch & Prof#=BeaverCTA,Main            , 1
Up Type= 0
Dn Type= 3
Dn Slope=0.007
Boundary for River Rch & Prof#=BeaverCTA,Main            , 2
Up Type= 0
Dn Type= 3
Dn Slope=0.007
Boundary for River Rch & Prof#=BeaverCTA,Main            , 3
Up Type= 0
Dn Type= 3
Dn Slope=0.007
Boundary for River Rch & Prof#=BeaverCTA,Main            , 4
Up Type= 0
Dn Type= 3
Dn Slope=0.007
Boundary for River Rch & Prof#=BeaverCTA,Main            , 5
Up Type= 0
Dn Type= 3
Dn Slope=0.007
Boundary for River Rch & Prof#=BeaverCTA,Main            , 6
Up Type= 0
Dn Type= 3
Dn Slope=0.007
DSS Import GetInterval= 0
DSS Import GetPeak= 0
DSS Import FillOption= 0

--- BeaverCTA.F02 (steady flow) ---

Flow Title=USGS Regression 100-10%,100-20%,100-35%
Program Version=4.10
Number of Profiles= 3
Profile Names=FC10,FC20,FC35
River Rch & RM=BeaverCTA,Main            ,14817.5
     820     820     990
River Rch & RM=BeaverCTA,Main            ,12672
     911     911    1101
River Rch & RM=BeaverCTA,Main            ,11148.5
     998     998    1205
River Rch & RM=BeaverCTA,Main            ,8031.6
    1109    1109    1340
River Rch & RM=BeaverCTA,Main            ,4645.7
    1218    1218    1471
Boundary for River Rch & Prof#=BeaverCTA,Main            , 1
Up Type= 0
Dn Type= 3
Dn Slope=0.007
Boundary for River Rch & Prof#=BeaverCTA,Main            , 2
Up Type= 0
Dn Type= 3
Dn Slope=0.007
Boundary for River Rch & Prof#=BeaverCTA,Main            , 3
Up Type= 0
Dn Type= 3
Dn Slope=0.007
DSS Import GetInterval= 0
DSS Import GetPeak= 0
DSS Import FillOption= 0

--- BeaverCTA.G01 (geometry) ---

Geom Title=Detailed Survey and LiDAR Data
Program Version=4.10

River Reach=BeaverCTA       ,Main
Reach XY= 30
     1999579.756      471619.158     1999910.441      471339.324
     2000231.453      470602.906     2000632.577      470341.373
     2000725.952      469992.119     2001089.331       469974.15
     2001631.929      469578.528     2001827.598      469330.835
     2001954.085      469317.143     2002182.443      468923.967
      2003043.01      467940.755     2003608.288      467794.295
      2004360.86      467973.573       2004807.5       467684.34
     2004893.084      466941.694     2005245.081      466713.931
      2005492.17      466342.608     2005517.017      466083.096
     2005358.273      465529.562     2005563.379      465307.164
     2005726.436      464840.069      2005680.56      464445.283
      2005867.13      464029.157     2005835.129      463911.344
     2006332.634      463546.335     2006773.403      462901.841
     2007123.142      462671.232     2007521.721      462691.614
     2007822.149       462495.48     2007951.901      462269.822

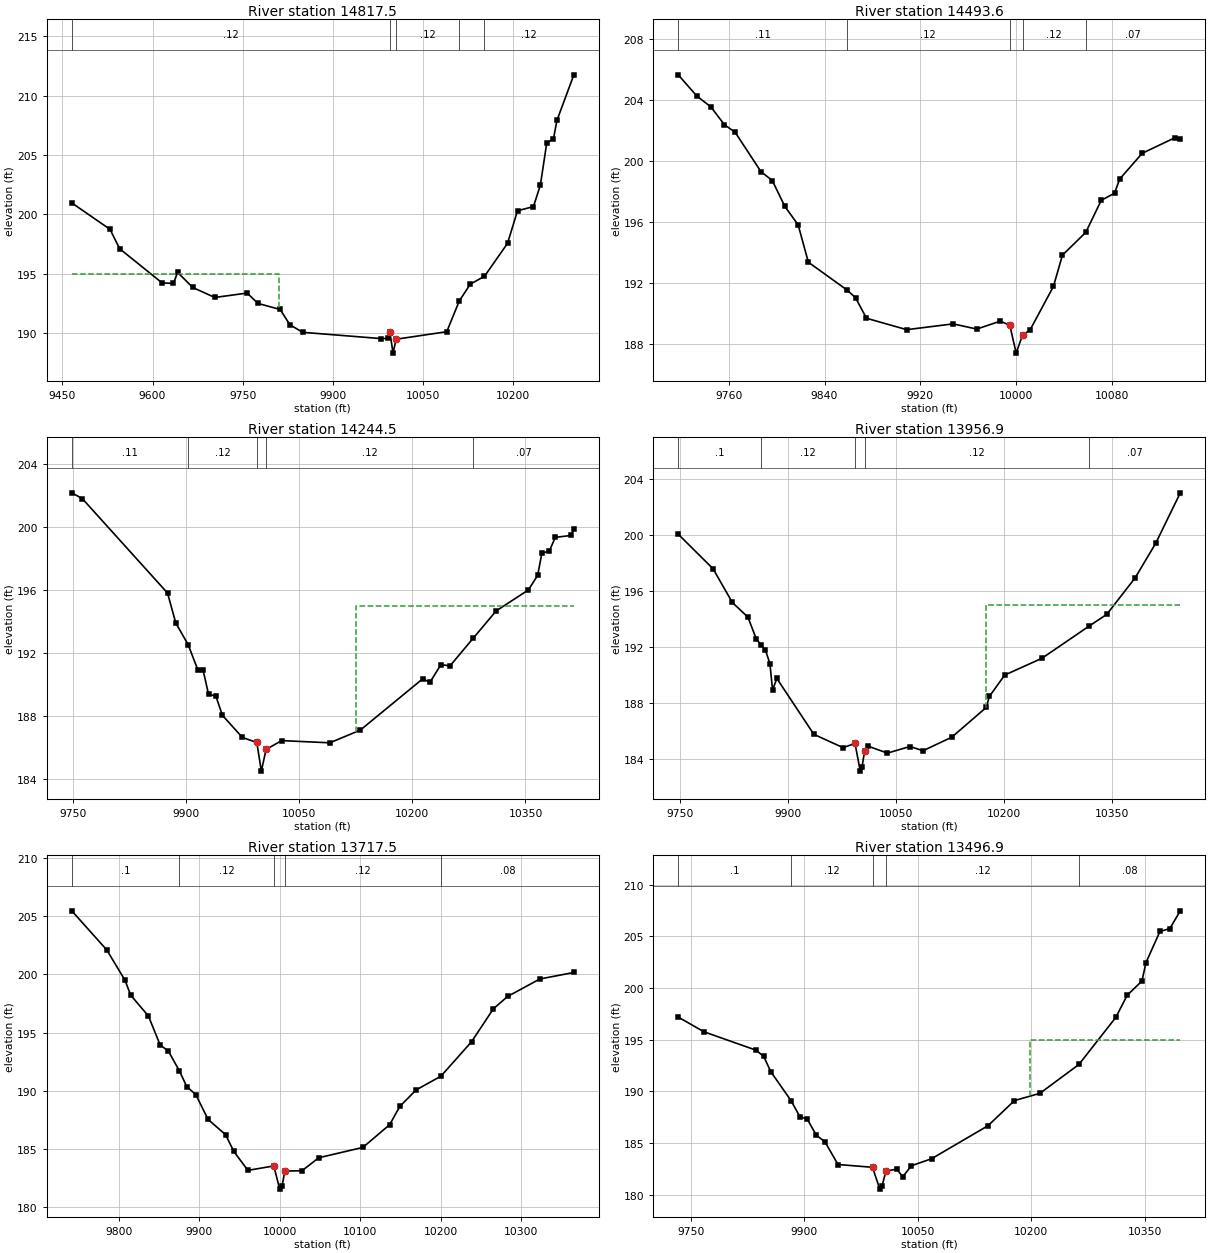
Type RM Length L Ch R = 1 ,14817.5 ,347.1,323.9,306.6
XS GIS Cut Line= 3
     1999799.734      472107.163     1999589.264       471616.06
     1999466.112      471341.766
#Sta/Elev= 30
  9465.7  200.97  9529.3  198.75  9545.3  197.12  9615.8  194.25  9634.8   194.2
  9641.7  195.13  9666.9  193.86  9703.5  193.02  9757.4  193.39  9775.3  192.52
  9812.3  192.01  9828.4  190.73  9849.6  190.09  9980.8  189.56  9991.7  189.58
  9994.8  190.09   10000  188.34 10005.2  189.51 10089.3  190.14 10110.2  192.73
 10128.5  194.14 10152.1   194.8 10190.4  197.57   10207  200.31 10233.5  200.66
 10245.1  202.48 10255.6  206.01 10266.8  206.36 10272.6  207.91 10300.7  211.74
#Mann= 5 ,-1 , 0
  9465.7     .12       0  9994.8    .045       0 10005.2     .12       0
 10110.2     .09       0 10152.1     .12       0
#XS Ineff= 2 , 0
       0    9811     195               0
Permanent Ineff=
       F       F
Bank Sta=9994.8,10005.2
XS Rating Curve= 0 ,0
Exp/Cntr=0.3,0.1

Type RM Length L Ch R = 1 ,14493.6 ,264.1,249.1,242.5
XS GIS Cut Line= 3
     2000025.969      471615.271      1999852.82      471430.558
     1999734.619      471314.165
#Sta/Elev= 30
  9717.9  205.68  9733.4  204.29  9745.1  203.58  9756.5   202.4  9765.4  201.91
  9786.9  199.33  9796.4  198.74  9806.9  197.04    9818  195.83  9826.5  193.38
  9858.5  191.57  9865.9  191.05    9875   189.7  9908.6  188.95  9947.4  189.33
  9967.1  188.99  9986.8  189.51  9994.7  189.23   10000  187.41 10005.3   188.6
 10011.5  188.92 10031.1  191.79 10038.6  193.84 10058.1  195.34   10071  197.44
 10082.1  197.91 10086.4  198.84 10105.2  200.53 10132.2  201.54   10137  201.45
#Mann= 5 ,-1 , 0
  9717.9     .11       0  9858.5     .12       0  9994.7    .045       0
 10005.3     .12       0 10058.1     .07       0
Bank Sta=9994.7,10005.3
XS Rating Curve= 0 ,0
Exp/Cntr=0.3,0.1

Type RM Length L Ch R = 1 ,14244.5 ,263.2,287.6,268
XS GIS Cut Line= 3
     2000206.482      471326.694     1999735.962      471099.071
     1999604.001      471045.036
#Sta/Elev= 30
  9748.8  202.18  9762.8  201.81  9875.7  195.81  9886.6  193.91    9903  192.53
  9915.9  190.92  9922.8  190.91    9930  189.38  9939.7  189.26  9948.4  188.04
  9974.9  186.63    9994  186.31   10000  184.49 10006.3  185.87 10026.9  186.43
 10090.8  186.29 10131.2   187.1 10213.9  190.36 10223.3  190.13   10238  191.26
   10250  191.18 10280.6  192.93 10311.1  194.67 10353.9  196.01 10366.1  196.93
 10371.7  198.33 10381.8   198.5 10389.5  199.35 10410.5  199.47 10414.1  199.88
#Mann= 5 ,-1 , 0
  9748.8     .11       0    9903     .12       0    9994    .045       0
 10006.3     .12       0 10280.6     .07       0
#XS Ineff= 2 , 0
       0                   10125       0     195
Permanent Ineff=
       F       F
Bank Sta=9994,10006.3
XS Rating Curve= 0 ,0
Exp/Cntr=0.3,0.1

Type RM Length L Ch R = 1 ,13956.9 ,225.5,239.4,223.8
XS GIS Cut Line= 4
     2000290.662      471093.658      2000041.13      470953.579
     1999742.295      470800.452     1999674.316       470766.97
#Sta/Elev= 30
  9747.1  200.08  9795.6   197.6  9822.2   195.2    9844  194.14  9855.6  192.58
    9862  192.18  9868.2   191.8  9874.5  190.82  9878.2  188.93  9884.1  189.76
  9935.6  185.76  9976.2  184.81  9992.8  185.11   10000  183.13 10002.6  183.45
 10006.1  184.58 10010.8  184.92 10037.7  184.42 10069.1  184.89 10087.3  184.59
 10127.3  185.56 10175.2  187.69 10179.4  188.47 10200.7     190 10252.4   191.2
 10318.2  193.51 10342.7  194.35 10382.2  196.97 10410.7  199.44 10444.8  203.04
#Mann= 5 ,-1 , 0
  9747.1      .1       0    9862     .12       0  9992.8    .045       0
 10006.1     .12       0 10318.2     .07       0
#XS Ineff= 2 , 0
       0                   10175       0     195
Permanent Ineff=
       F       F
Bank Sta=9992.8,10006.1
XS Rating Curve= 0 ,0
Exp/Cntr=0.3,0.1

Type RM Length L Ch R = 1 ,13717.5 ,201.4,220.6,222.4
XS GIS Cut Line= 3
     2000393.869      470886.727     1999954.434      470655.684
     1999837.321      470605.564
#Sta/Elev= 30
  9741.6  205.45  9785.1  202.09  9807.8  199.48  9814.7  198.22  9836.8  196.42
  9851.3  193.95  9861.7   193.4  9875.2  191.72  9884.4  190.37  9895.6  189.68
  9910.9  187.55  9932.6  186.24  9942.8  184.81  9960.3  183.18  9992.5  183.56
  9999.8  181.57 10002.8  181.85 10006.2  183.12 10027.5  183.15 10048.3  184.26
 10103.1  185.15 10136.4   187.1   10149  188.67 10169.4  190.09   10200  191.26
 10238.1  194.22 10265.1  197.04 10282.8   198.1 10322.8   199.6 10365.1  200.16
#Mann= 5 ,-1 , 0
  9741.6      .1       0  9875.2     .12       0  9992.5    .045       0
 10006.2     .12       0   10200     .08       0
Bank Sta=9992.5,10006.2
XS Rating Curve= 0 ,0
Exp/Cntr=0.3,0.1

Type RM Length L Ch R = 1 ,13496.9 ,190.3,206.7,221.1
XS GIS Cut Line= 4
     2000480.303      470745.377     2000288.301      470602.339
     2000081.198      470438.561      1999956.05      470338.933
#Sta/Elev= 30
  9733.7  197.19  9767.6  195.77  9836.5  193.99  9846.6  193.39  9856.1   191.9
  9882.7  189.12  9894.3  187.58  9904.3   187.3  9916.2  185.77  9927.6  185.13
  9944.8  182.94  9990.4  182.67   10000  180.56 10003.1  180.87 10008.1   182.3
 10022.4  182.49 10030.4  181.76 10041.8  182.82 10068.5   183.5   10143  186.69
   10178  189.12 10211.6  189.82 10263.1  192.61 10311.9  197.16 10326.9   199.3
 10346.4  200.67 10351.7  202.45 10370.2  205.47 10383.2  205.74 10397.1  207.46
#Mann= 5 ,-1 , 0
  9733.7      .1       0  9882.7     .12       0  9990.4    .045       0
 10008.1     .12       0 10263.1     .08       0
#XS Ineff= 2 , 0
       0                   10198       0     195
Permanent Ineff=
       F       F
Bank Sta=9990.4,10008.1
XS Rating Curve= 0 ,0
Exp/Cntr=0.3,0.1

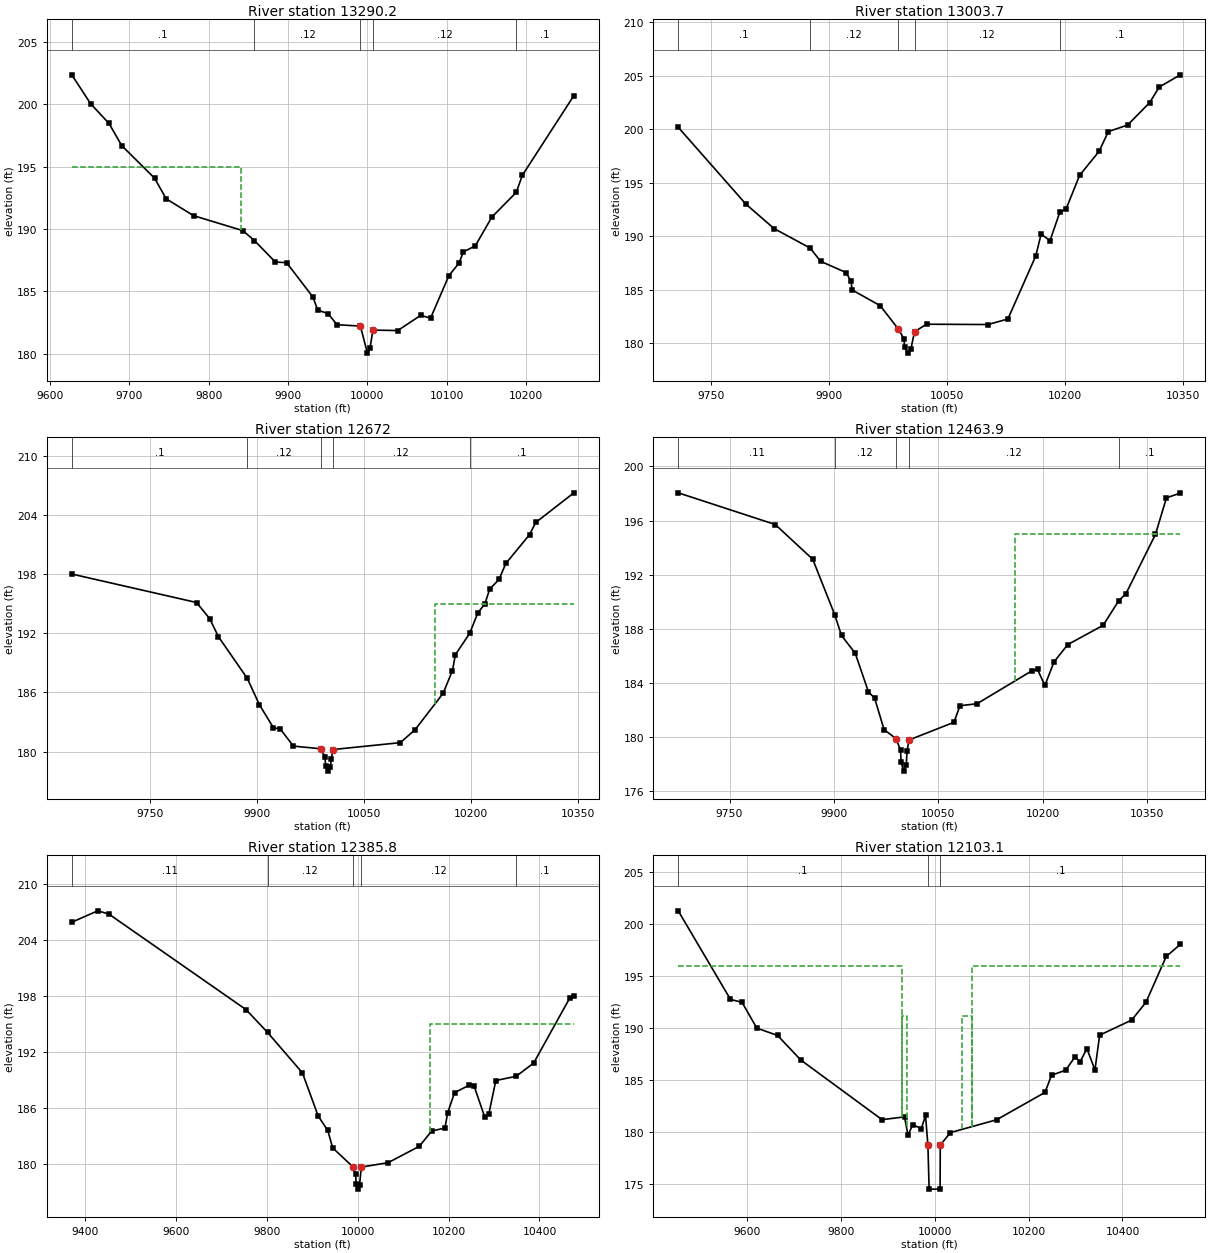
Type RM Length L Ch R = 1 ,13290.2 ,288.2,286.5,234.7
XS GIS Cut Line= 3
     2000591.614      470755.784     2000518.432      470632.854
      2000265.96      470212.066
#Sta/Elev= 30
  9627.3  202.37  9651.1  200.05  9674.2  198.47  9690.3  196.69  9731.6  194.08
  9746.4  192.42  9780.8  191.07  9842.9  189.87  9857.6  189.07  9883.9  187.35
  9898.1   187.3  9931.3  184.54  9937.3   183.5  9950.6   183.2  9961.6  182.32
  9991.1  182.21   10000  180.04 10003.2  180.43 10006.9  181.89 10038.2  181.85
 10067.1  183.07 10079.6  182.85 10102.7  186.26 10115.4  187.26   10121  188.17
 10135.9  188.64 10156.8  190.95 10187.6  192.94 10195.3  194.31 10260.2   200.7
#Mann= 5 ,-1 , 0
  9627.3      .1       0  9857.6     .12       0  9991.1    .045       0
 10006.9     .12       0 10187.6      .1       0
#XS Ineff= 2 , 0
       0    9840     195               0
Permanent Ineff=
       F       F
Bank Sta=9991.1,10006.9
XS Rating Curve= 0 ,0
Exp/Cntr=0.3,0.1

Type RM Length L Ch R = 1 ,13003.7 ,314,331.7,328.7
XS GIS Cut Line= 4
     2000866.484      470485.708     2000762.443      470409.221
     2000614.384      470297.719     2000339.734      470124.712
#Sta/Elev= 30
  9708.3  200.18  9794.4     193  9830.2  190.72  9876.1   188.9  9889.2  187.67
  9921.8  186.61    9928  185.78  9929.4  184.99  9965.1  183.52  9988.3  181.32
  9995.1  180.44  9996.2  179.65   10000  179.09 10004.1  179.49 10008.7  181.09
   10024  181.79 10102.2  181.76 10127.4  182.28 10162.8  188.16 10169.6   190.2
   10181   189.6 10193.5  192.27 10201.2  192.52 10218.6   195.7 10243.3  197.93
 10255.1  199.78 10279.6  200.39 10307.7  202.49 10319.8  203.94 10346.6  205.08
#Mann= 5 ,-1 , 0
  9708.3      .1       0  9876.1     .12       0  9988.3    .045       0
 10008.7     .12       0 10193.5      .1       0
Bank Sta=9988.3,10008.7
XS Rating Curve= 0 ,0
Exp/Cntr=0.3,0.1

Type RM Length L Ch R = 1 ,12672   ,175.7,208.1,255.4
XS GIS Cut Line= 4
     2000975.154      470252.389     2000869.213      470142.612
     2000575.457      469863.038     2000460.572      469771.366
#Sta/Elev= 30
  9640.6  198.01  9815.6  195.12  9834.1  193.48  9846.2  191.66  9886.8  187.42
  9903.6  184.77  9923.5   182.4  9932.9   182.3  9951.4  180.55  9989.6  180.28
  9995.7  179.48  9996.6  178.56   10000  178.01 10003.4  178.43 10004.3  179.21
   10007   180.2 10101.4   180.9 10122.2  182.22 10161.4   185.9 10174.6  188.22
 10178.6  189.82 10198.7  191.99 10210.1  194.06 10220.1     195 10226.7  196.47
 10239.8  197.46 10249.4  199.08 10282.7  202.01 10291.3  203.24 10344.8  206.25
#Mann= 5 ,-1 , 0
  9640.6      .1       0  9886.8     .12       0  9989.6    .045       0
   10007     .12       0 10198.7      .1       0
#XS Ineff= 2 , 0
       0                   10150       0     195
Permanent Ineff=
       F       F
Bank Sta=9989.6,10007
XS Rating Curve= 0 ,0
Exp/Cntr=0.3,0.1

Type RM Length L Ch R = 1 ,12463.9 ,77.9,78.1,78.2
XS GIS Cut Line= 5
     2001003.919      470274.762      2000925.03      470087.058
     2000910.525      469800.749     2000784.367      469681.807
     2000738.771      469646.883
#Sta/Elev= 30
  9676.3  198.05  9815.6  195.71  9869.5  193.14    9901  189.05  9910.8  187.51
  9930.5   186.2  9949.5  183.34  9958.3  182.89  9971.9  180.56  9989.1  179.89
  9995.6  179.03  9996.4  178.16   10000  177.49 10003.8  177.93 10004.9  178.96
 10007.7  179.79 10072.4   181.1 10080.9  182.32 10105.5  182.47 10183.8  184.89
 10192.3     185 10202.9  183.82   10216  185.56 10235.8  186.84 10286.5  188.26
   10309  190.08 10319.2  190.59 10361.7  194.98 10377.5  197.68 10397.4  198.03
#Mann= 5 ,-1 , 0
  9676.3     .11       0    9901     .12       0  9989.1    .045       0
 10007.7     .12       0   10309      .1       0
#XS Ineff= 2 , 0
       0                   10160       0     195
Permanent Ineff=
       F       F
Bank Sta=9989.1,10007.7
XS Rating Curve= 0 ,0
Exp/Cntr=0.3,0.1

Type RM Length L Ch R = 1 ,12385.8 ,320.5,282.7,232.2
XS GIS Cut Line= 4
     2001280.795      470519.267     2001002.558      470094.423
     2000986.986      469761.181     2000750.024       469643.42
#Sta/Elev= 30
  9370.1  205.91  9427.3  207.13  9451.6  206.79  9753.9  196.55  9801.2  194.11
    9878  189.78  9912.8  185.15  9933.9  183.61  9944.6  181.75  9988.7  179.74
  9995.2  178.93  9996.3  177.87   10000  177.33 10003.8  177.79 10007.7  179.69
 10066.6  180.16 10135.6  181.92 10162.4  183.54 10191.9  183.88 10197.8  185.49
   10213  187.66 10245.3  188.46 10255.9  188.39 10279.2  185.09 10288.6  185.41
 10303.9  188.96 10348.5  189.41 10387.2  190.83 10466.8   197.8 10475.7     198
#Mann= 5 ,-1 , 0
  9370.1     .11       0  9801.2     .12       0  9988.7    .045       0
 10007.7     .12       0 10348.5      .1       0
#XS Ineff= 2 , 0
       0                   10160       0     195
Permanent Ineff=
       F       F
Bank Sta=9988.7,10007.7
XS Rating Curve= 0 ,0
Exp/Cntr=0.5,0.3

Type RM Length L Ch R = 1 ,12103.1 ,181.4,183.3,188.1
BEGIN DESCRIPTION:
Intersected Profiles were noted internally, and could not be removed using standard engineering practice.
END DESCRIPTION:
XS GIS Cut Line= 6
     2001740.849      470052.935     2001512.714      469969.639
     2001299.335      469881.803      2001206.01      469841.678
      2000990.32      469744.778     2000756.949      469635.629
#Sta/Elev= 30
    9454  201.26  9565.2  192.74  9589.8  192.46  9621.3  189.98  9665.6  189.27
    9715  186.91    9888  181.17  9935.9  181.44  9943.4  179.66  9953.3   180.7
  9971.7   180.3  9980.6  181.58  9985.7   178.7  9988.3  174.4910011.65  174.49
   10012  178.72 10033.6  179.93 10131.9  181.16 10234.9  183.79 10249.1  185.45
 10279.1  185.93 10299.2  187.23 10309.8  186.73 10324.2  188.01 10341.4  185.96
 10351.4   189.3 10419.6  190.75   10450  192.46 10493.2  196.87 10523.2  198.03
#Mann= 3 ,-1 , 0
    9454      .1       0  9985.7    .045       0   10012      .1       0
#XS Ineff= 4 ,-1
    9454    9930     196    9930    9941  191.18   10058   10080  191.18
   10080 10523.2     196
Permanent Ineff=
       F       F       F       F
Bank Sta=9985.7,10012
XS Rating Curve= 0 ,0
Exp/Cntr=0.5,0.3

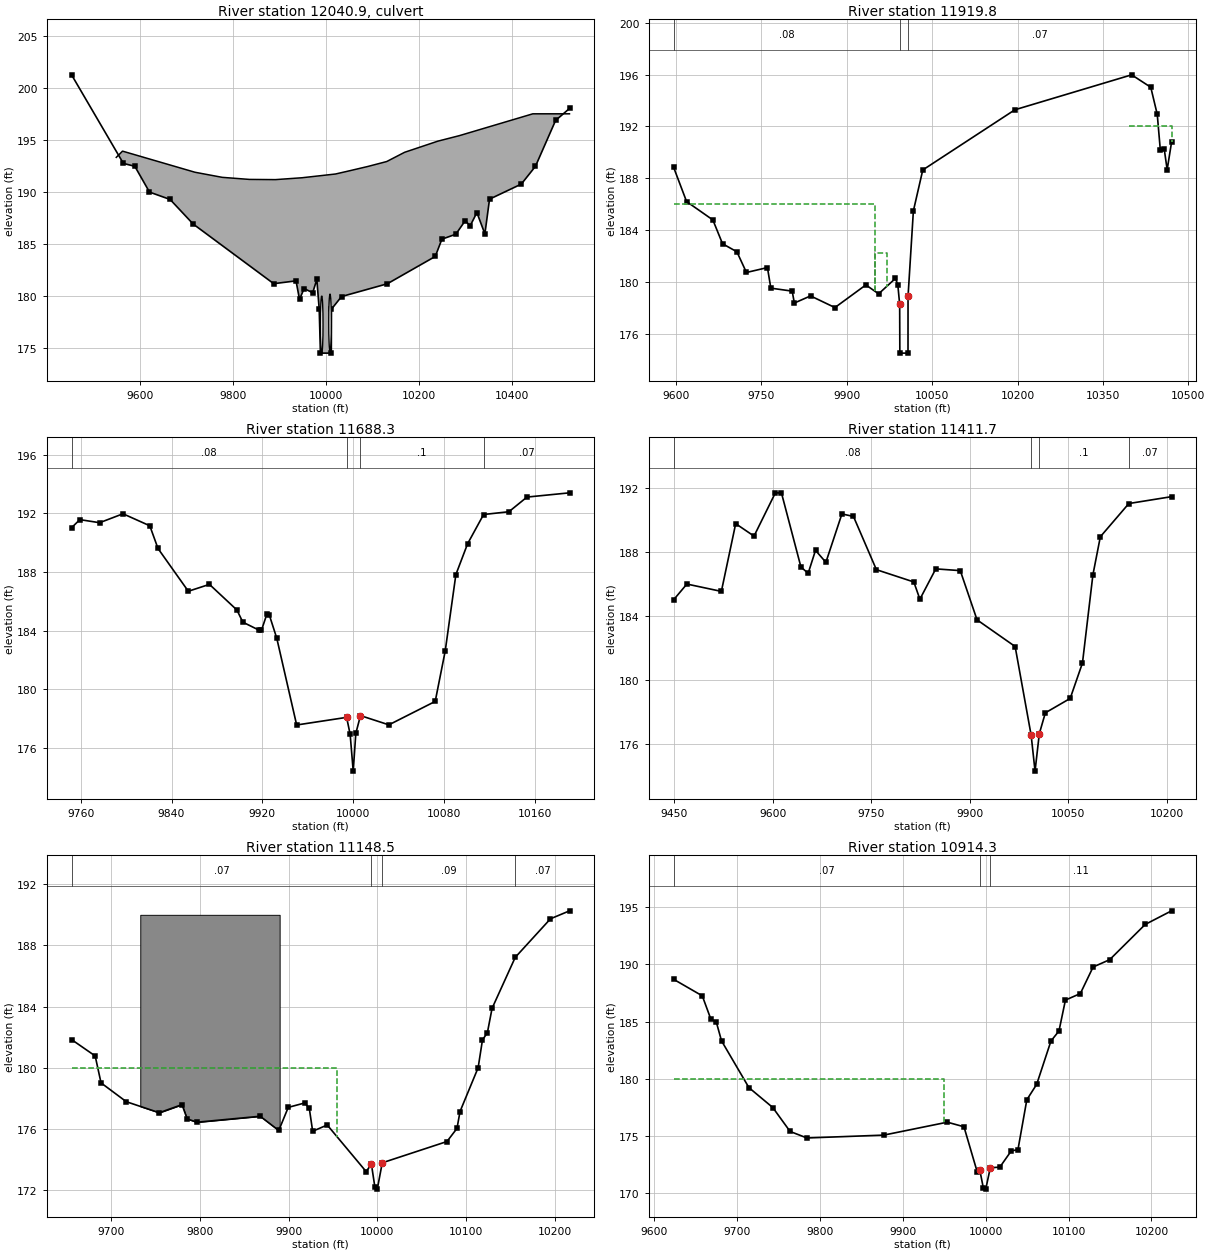
Type RM Length L Ch R = 2 ,12040.9 ,,,
BEGIN DESCRIPTION:
370076-0009 Culvert: US 401 Raeford Road
END DESCRIPTION:
Bridge Culvert--1,0,-1,-1, 0
Deck Dist Width WeirC Skew NumUp NumDn MinLoCord MaxHiCord MaxSubmerge Is_Ogee
47,79,2.6,0, 16, 16, 191.18, , 0.95, 0, 0,0,,
    9550  9563.4  9718.9  9777.4  9835.8  9891.8  9948.8 10020.6 10050.7 10090.5
 10130.6 10169.1 10240.4 10286.6 10444.3   10523
  193.32  193.92  191.89   191.4   191.2  191.18  191.36  191.72  192.03  192.45
  192.92  193.81  194.88  195.41  197.51  197.51
                                                                                
                                                
    9550  9563.4  9718.9  9777.4  9835.8  9891.8  9948.8 10020.6 10050.7 10090.5
 10130.6 10169.1 10240.4 10286.6 10444.3   10523
  193.32  193.92  191.89   191.4   191.2  191.18  191.36  191.72  192.03  192.45
  192.92  193.81  194.88  195.41  197.51  197.51
                                                                                
                                                
BR Coef=-1 , 0 , 0 ,, 0 ,,,0.8,-1,,0,
WSPro=,,,, 1 ,,,, 0 ,,,, 0 ,,,,-1 ,-1 ,-1 , 0 , 0 , 0 , 0 , 0
Culvert=1,5.5,,161,0.013,0.5,1,1,1,174.49,9991.1,174.68,9996.1,Culvert #1  , 0 ,15
Culvert Bottom n=0.013
Culvert=1,5.5,,164.4,0.013,0.5,1,1,1,174.68,10008.9,174.49,10004.8,Culvert #2  , 0 ,8.4
Culvert Bottom n=0.013
BC Design=,, 0 ,, 0 ,,,,,,
BC Use User HTab Curves=0
BC User HTab FreeFlow(D)= 0

Type RM Length L Ch R = 1 ,11919.8 ,232.3,231.5,224.8
XS GIS Cut Line= 6
     2001742.576      469876.683     2001596.683      469823.082
     2001488.681      469779.636     2001384.845      469735.874
     2001183.566      469647.593     2000936.816       469535.79
#Sta/Elev= 30
  9595.5  188.86  9618.4   186.2  9664.6  184.78  9681.6  182.94  9706.8  182.32
  9723.6  180.72  9760.5   181.1  9766.5  179.51    9804  179.28  9807.8  178.36
  9836.3  178.91  9879.1  178.01  9933.5  179.76  9955.9  179.07  9985.4  180.26
  9989.6  179.79  9992.9  178.25  9993.2  174.4910007.55  174.49 10007.6  178.87
   10017  185.48 10033.5  188.64 10195.4  193.29 10400.6  195.99 10434.2  195.03
 10445.6  192.93   10451  190.17 10457.9  190.24   10463  188.66 10470.7  190.78
#Mann= 3 ,-1 , 0
  9595.5     .08       0  9992.9    .045       0 10007.6     .07       0
#XS Ineff= 4 ,-1
  9595.5    9950     186    9950 9969.85   182.210031.05 10396.8   182.2
 10396.8 10470.7     192
Permanent Ineff=
       F       F       F       F
Bank Sta=9992.9,10007.6
XS Rating Curve= 0 ,0
Exp/Cntr=0.5,0.3

Type RM Length L Ch R = 1 ,11688.3 ,274.9,276.6,272.4
XS GIS Cut Line= 5
     2001750.716      469795.733      2001695.24      469743.639
     2001497.928      469563.998     2001477.496      469545.395
     2001460.559       469479.61
#Sta/Elev= 30
    9752  191.02  9759.3  191.57  9776.7  191.36  9797.3  191.97  9820.9  191.15
  9828.1   189.6  9854.8  186.68  9873.4  187.15  9897.6   185.4  9902.8  184.57
  9917.2  184.02  9919.2  184.01  9924.1  185.15  9926.2  185.04  9932.7  183.47
  9950.2  177.55  9994.2  178.07  9997.3  176.91   10000   174.4 10002.3  176.98
 10006.4  178.19 10031.4  177.56 10072.2  179.16   10081   182.6 10090.4  187.82
 10100.7  189.92 10114.8  191.92 10137.1  192.11   10153  193.11 10190.5   193.4
#Mann= 4 ,-1 , 0
    9752     .08       0  9994.2    .045       0 10006.4      .1       0
 10114.8     .07       0
Bank Sta=9994.2,10006.4
XS Rating Curve= 0 ,0
Exp/Cntr=0.3,0.1

Type RM Length L Ch R = 1 ,11411.7 ,255.8,263.2,217.8
XS GIS Cut Line= 6
     2002060.499      469791.718     2001985.976      469760.881
      2001827.38      469694.686     2001807.617       469471.79
     2001670.335      469358.566     2001604.661      469278.107
#Sta/Elev= 30
  9449.2  185.02  9469.5  186.01    9522  185.55  9543.8  189.79  9571.7  189.01
  9604.2  191.72  9613.5  191.71  9643.1  187.08  9654.1  186.68  9665.3  188.12
  9681.1  187.37  9705.5   190.4  9723.1  190.24    9758  186.91    9815  186.14
  9824.2  185.06  9848.4  186.96  9885.7  186.85  9911.2  183.77  9969.2   182.1
  9993.6  176.54  9999.5   174.3   10006  176.64 10015.2  177.95   10053  178.85
 10071.7  181.07 10087.6  186.59 10098.9  188.97 10142.3  191.05 10207.3  191.48
#Mann= 4 ,-1 , 0
  9449.2     .08       0  9993.6    .045       0   10006      .1       0
 10142.3     .07       0
Bank Sta=9993.6,10006
XS Rating Curve= 0 ,0
Exp/Cntr=0.3,0.1

Type RM Length L Ch R = 1 ,11148.5 ,226.7,234.2,223.8
XS GIS Cut Line= 3
     2002234.026      469517.565     2001853.421      469240.689
      2001783.32      469183.772
#Sta/Elev= 30
  9655.6  181.85  9682.2  180.78  9688.8  179.02  9717.3  177.79  9754.4  177.07
    9780   177.6  9785.8  176.67  9796.8  176.45  9868.1  176.84    9889  175.91
  9899.7  177.42  9918.3  177.71  9923.4  177.36  9927.2  175.86  9943.6  176.27
  9987.4  173.23  9993.4   173.7  9997.3  172.21   10000  172.08 10005.6   173.8
 10078.5  175.19 10089.8  176.05 10093.2  177.15 10113.6  180.01 10118.5  181.83
   10124  182.29 10129.3  183.89 10155.4  187.22 10195.1  189.74 10216.6  190.26
#Mann= 4 ,-1 , 0
  9655.6     .07       0  9993.4    .045       0 10005.6     .09       0
 10155.4     .07       0
#XS Ineff= 2 , 0
       0    9955     180               0
Permanent Ineff=
       F       F
#Block Obstruct= 1 ,-1
    9733    9890     190
Bank Sta=9993.4,10005.6
XS Rating Curve= 0 ,0
Exp/Cntr=0.3,0.1

Type RM Length L Ch R = 1 ,10914.3 ,279.2,281.7,282.9
XS GIS Cut Line= 3
     2002369.205      469334.739     2001909.343      469018.432
     2001875.279      468991.668
#Sta/Elev= 30
  9623.1   188.7  9657.8  187.25    9668  185.24  9674.8  184.94    9681  183.32
  9714.1  179.23  9742.9  177.49  9763.8   175.4  9784.1  174.83  9876.9  175.08
  9953.6  176.21  9973.7  175.81  9989.8  171.84  9992.8  172.03  9997.1  170.46
   10000  170.36 10005.5  172.23   10017  172.28 10030.7  173.69 10038.9  173.82
 10049.6  178.17 10061.5  179.52 10078.7   183.3 10088.4  184.18 10096.2  186.88
 10114.2  187.45 10129.6  189.77 10149.6  190.41 10192.5  193.49 10224.3  194.68
#Mann= 3 ,-1 , 0
  9623.1     .07       0  9992.8    .045       0 10005.5     .11       0
#XS Ineff= 2 , 0
       0    9950     180               0
Permanent Ineff=
       F       F
Bank Sta=9992.8,10005.5
XS Rating Curve= 0 ,0
Exp/Cntr=0.3,0.1

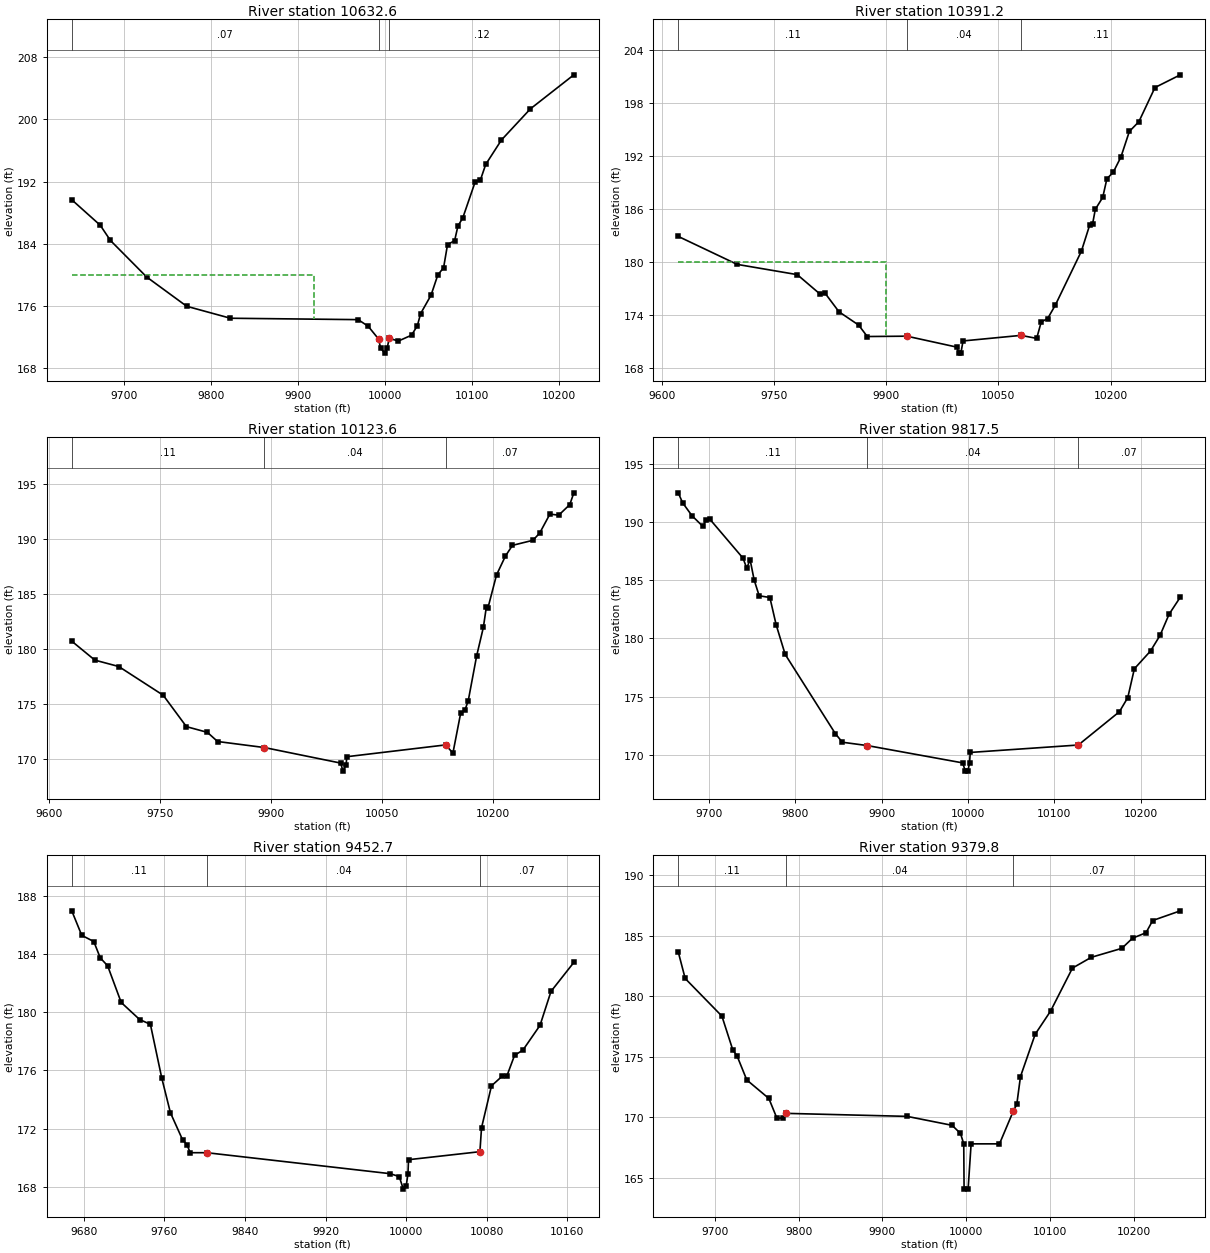
Type RM Length L Ch R = 1 ,10632.6 ,266,241.4,232.5
BEGIN DESCRIPTION:
drawdowns exist and could not be removed using standard engineering practice
END DESCRIPTION:
XS GIS Cut Line= 3
     2002462.239      469142.458     2002358.914      469008.524
      2002045.41      468748.315
#Sta/Elev= 30
  9640.2  189.65  9672.9  186.37  9684.6  184.41  9726.2  179.71  9772.2  175.94
  9822.4   174.4  9969.1  174.22  9980.6  173.37  9992.5  171.73  9994.9  170.57
  9999.4  169.91 10002.4  170.52 10004.7  171.81 10015.4  171.47 10030.4  172.22
 10037.1  173.44 10040.8  174.99 10052.8  177.37 10060.6  179.98 10067.2   180.9
 10071.7  183.86 10079.9   184.4 10083.7  186.28 10089.2   187.3 10103.6  191.99
 10109.5   192.2 10115.6   194.2 10133.7  197.35 10166.9  201.35 10216.8  205.73
#Mann= 3 ,-1 , 0
  9640.2     .07       0  9992.5    .045       0 10004.7     .12       0
#XS Ineff= 2 , 0
       0    9918     180               0
Permanent Ineff=
       F       F
Bank Sta=9992.5,10004.7
XS Rating Curve= 0 ,0
Exp/Cntr=0.3,0.1

Type RM Length L Ch R = 1 ,10391.2 ,283.2,267.6,273
XS GIS Cut Line= 3
     2002681.409      468969.875     2002393.714      468731.413
     2002149.793      468561.042
#Sta/Elev= 30
  9622.2  182.85    9701  179.68  9781.3  178.52    9812   176.3  9818.6   176.4
  9837.1  174.31  9863.3  172.81  9874.9  171.51  9927.8  171.55  9994.6  170.31
  9997.2  169.63   10000  169.64 10002.9  171.01 10080.3  171.64 10101.3   171.3
 10107.4  173.16   10116  173.55 10126.2  175.06 10161.1  181.18 10172.1  184.12
 10176.1  184.29 10179.7  185.92 10189.6  187.27 10195.2  189.39 10203.5  190.09
 10213.9  191.84 10225.2  194.74 10237.9  195.84 10259.4  199.71 10293.3  201.15
#Mann= 3 ,-1 , 0
  9622.2     .11       0  9927.8     .04       0 10080.3     .11       0
#XS Ineff= 2 , 0
       0    9900     180               0
Permanent Ineff=
       F       F
Bank Sta=9927.8,10080.3
XS Rating Curve= 0 ,0
Exp/Cntr=0.3,0.1

Type RM Length L Ch R = 1 ,10123.6 ,327.4,306.1,314.4
XS GIS Cut Line= 2
     2002860.521      468742.045     2002311.888       468340.76
#Sta/Elev= 30
  9630.2   180.7  9661.4  178.98  9693.8   178.4    9754  175.79  9785.4  172.94
  9813.8  172.42  9827.6  171.59  9891.1  171.04  9994.3  169.63  9997.3   168.9
 10001.5  169.44 10002.6  170.21 10136.3  171.28 10146.2  170.54 10156.7  174.17
 10162.4  174.44 10166.9  175.28 10178.3  179.36 10187.4  181.95 10191.4  183.78
 10193.5  183.69 10205.2  186.71 10217.3  188.43 10226.8   189.4 10254.5  189.86
 10263.6  190.51 10277.5  192.24 10289.4  192.14 10304.4   193.1 10309.9  194.17
#Mann= 3 ,-1 , 0
  9630.2     .11       0  9891.1     .04       0 10136.3     .07       0
Bank Sta=9891.1,10136.3
XS Rating Curve= 0 ,0
Exp/Cntr=0.3,0.1

Type RM Length L Ch R = 1 ,9817.5  ,346,364.8,384.2
XS GIS Cut Line= 3
      2003024.09      468494.942     2002758.902      468289.403
     2002568.367      468134.139
#Sta/Elev= 30
  9664.5  192.55  9669.6  191.69  9680.4  190.58  9693.1  189.65  9696.5  190.18
  9701.3  190.26  9739.5  186.92  9743.8  186.06  9747.7  186.79  9752.4  185.04
  9758.2  183.68  9770.6  183.53  9777.9  181.17  9788.3  178.63  9846.4   171.8
  9854.5  171.06  9883.6  170.77  9993.8  169.28  9996.9  168.57   10000  168.61
 10001.8  169.31 10002.6  170.18 10127.7  170.82 10175.3  173.69   10185  174.91
 10192.6  177.39 10211.3  178.92 10222.3  180.26 10232.8  182.09 10245.8  183.56
#Mann= 3 ,-1 , 0
  9664.5     .11       0  9883.6     .04       0 10127.7     .07       0
Bank Sta=9883.6,10127.7
XS Rating Curve= 0 ,0
Exp/Cntr=0.3,0.1

Type RM Length L Ch R = 1 ,9452.7  ,83.1,72.9,72.8
XS GIS Cut Line= 3
     2003206.746      468257.346     2003142.285      468174.467
     2002877.074      467883.472
#Sta/Elev= 30
  9667.9  186.95  9677.8  185.27  9689.8  184.84  9696.2  183.72  9703.5  183.18
    9717  180.66  9735.3  179.49    9746  179.16  9757.3  175.47  9765.9  173.09
    9778  171.23  9782.3  170.91  9785.5  170.35    9802  170.35  9984.2  168.91
  9993.2  168.71  9997.2  167.85   10000  168.04 10001.8  168.88 10002.4  169.87
 10073.3  170.42 10074.9  172.06 10084.8  174.94 10095.4   175.6 10100.2  175.64
 10107.7  177.03   10116  177.39   10133  179.09 10143.9  181.42 10166.6  183.41
#Mann= 3 ,-1 , 0
  9667.9     .11       0    9802     .04       0 10073.3     .07       0
Bank Sta=9802,10073.3
XS Rating Curve= 0 ,0
Exp/Cntr=0.5,0.3

Type RM Length L Ch R = 1 ,9379.8  ,310.2,85.3,130.3
XS GIS Cut Line= 6
      2003262.68      468205.391     2003219.207       468132.97
     2003076.301      467985.818     2002919.933      467832.747
     2002898.349      467794.175     2002868.624      467757.551
#Sta/Elev= 30
  9655.9  183.68  9664.2  181.48  9708.1  178.37    9721   175.6  9726.4  175.05
  9737.8   173.1  9764.2  171.57  9773.8  169.94  9781.5  169.96  9784.3  170.34
  9929.4  170.09  9983.2  169.35  9993.2  168.68  9997.1  167.82  9997.5  164.08
 10002.3  164.08 10005.9  167.82 10039.8  167.82 10056.3  170.52 10060.5  171.09
 10064.9  173.38 10082.5  176.88 10100.8  178.78   10127  182.34 10149.5  183.23
   10186  183.97 10198.8  184.81 10214.9  185.26 10222.9  186.27 10255.9  187.07
#Mann= 3 ,-1 , 0
  9655.9     .11       0  9784.3     .04       0 10056.3     .07       0
Bank Sta=9784.3,10056.3
XS Rating Curve= 0 ,0
Exp/Cntr=0.5,0.3