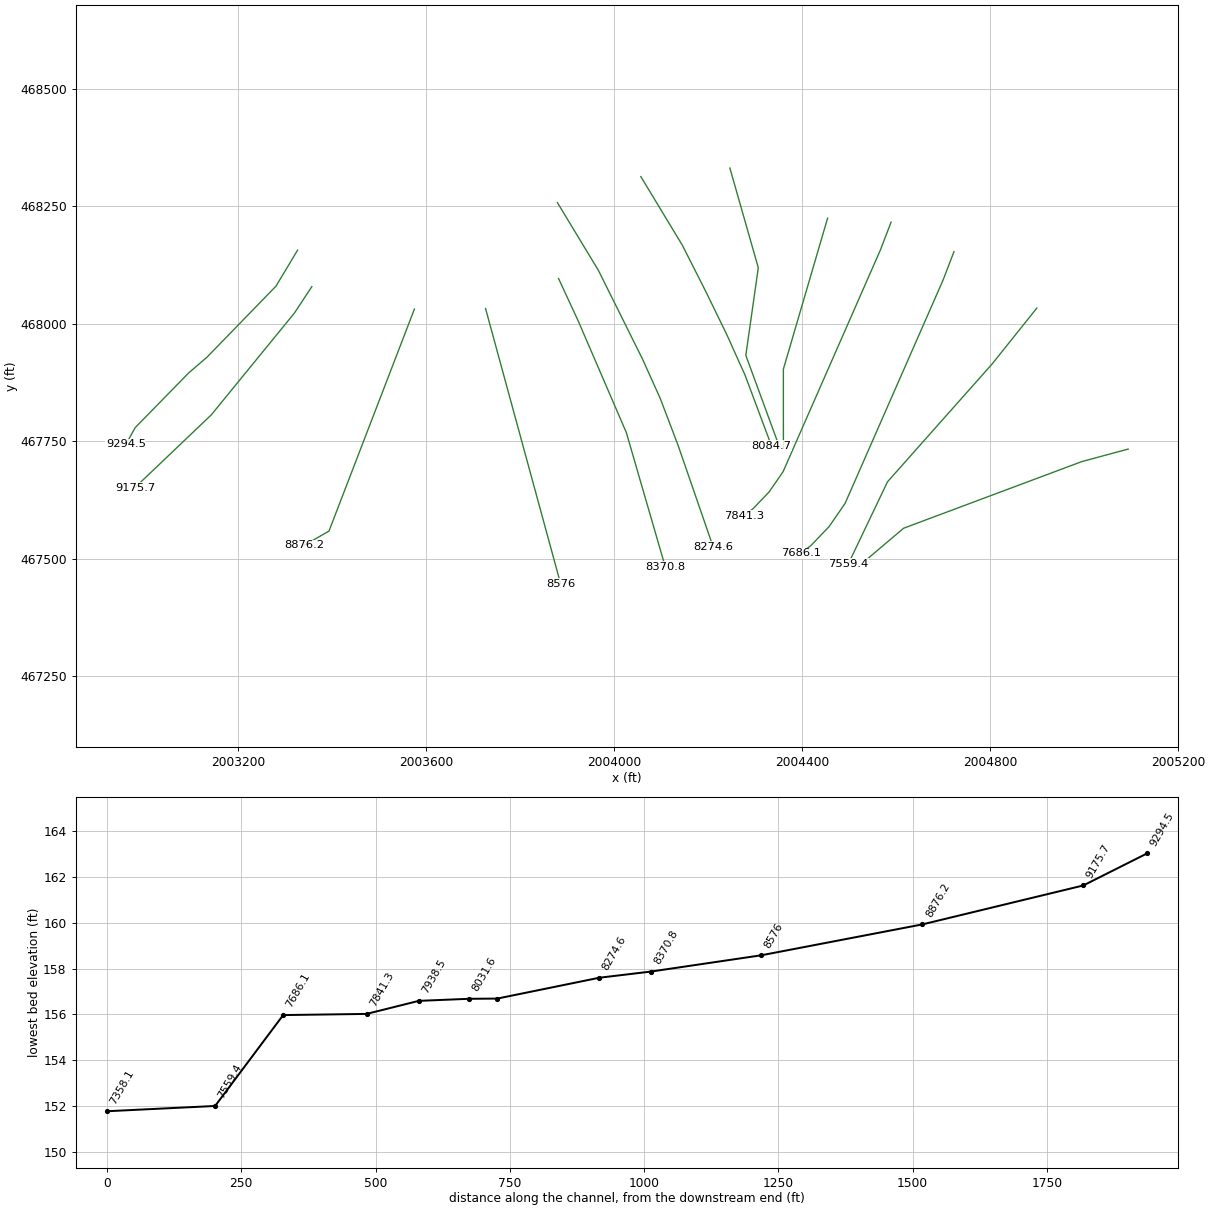
HEC-RAS study BeaverCTA.PRJ: BeaverCTA

--- BeaverCTA.G01 (geometry) --- (continued)

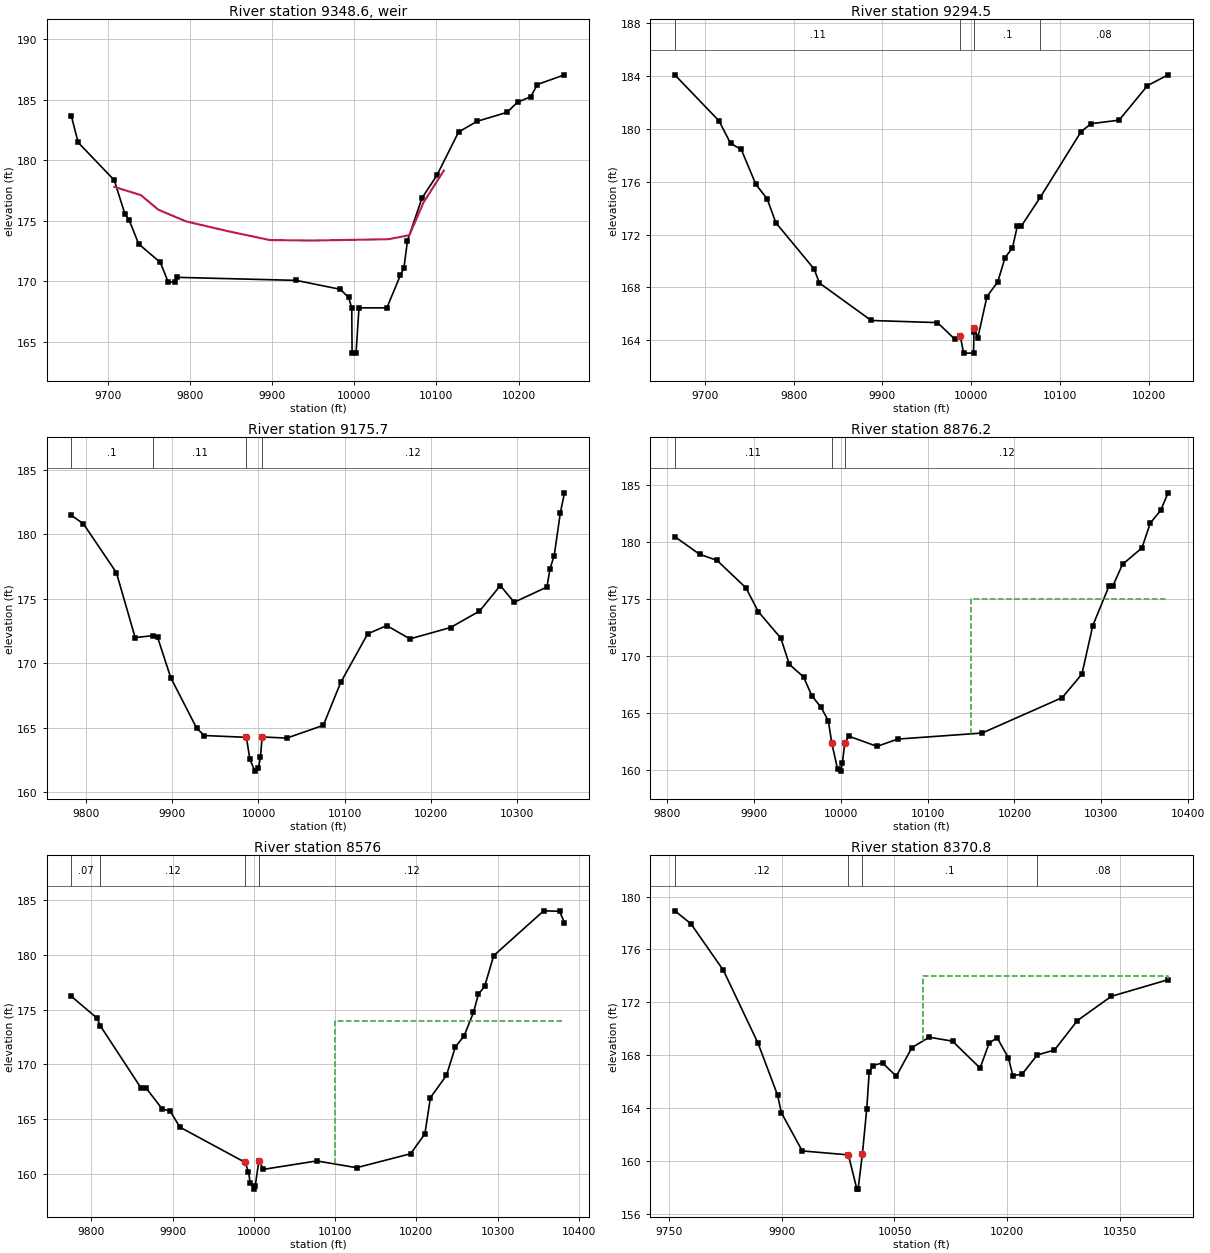
Type RM Length L Ch R = 5 ,9348.6  ,,,
BEGIN DESCRIPTION:
370076-0010 Culvert: Earth Dam
END DESCRIPTION:
IW Pilot Flow=0
#Inline Weir SE= 11
  9708.4  177.81  9740.6  177.13  9761.9  175.92  9795.6  174.96  9846.6  174.15
  9897.6  173.42  9948.6  173.38 10041.5  173.49 10067.1  173.82 10084.5  176.54
 10109.1  179.16
IW Dist,WD,Coef,Skew,MaxSub,Min_El,Is_Ogee,SpillHt,DesHd
21,15,2.6,0,0.98,, 0 ,,,0,0,

Type RM Length L Ch R = 1 ,9294.5  ,101.7,118.8,93.5
XS GIS Cut Line= 6
     2003326.077      468157.077     2003280.057      468080.411
     2003133.424      467929.431     2003094.593       467896.02
     2002980.552       467779.43     2002960.678      467743.912
#Sta/Elev= 30
  9666.4  184.08  9716.1   180.6  9729.1   178.9  9741.1  178.44  9757.5  175.81
  9770.3   174.7    9780   172.9  9823.2  169.39    9829  168.34  9887.4   165.5
    9962  165.34  9981.6  164.08  9987.8  164.29  9991.4  163.03 10002.6  163.03
 10003.1  164.63 10003.6  164.93 10007.4  164.18 10017.7  167.31 10029.9  168.43
 10038.1  170.26 10046.4  170.99 10051.9  172.64 10056.4  172.64 10077.7  174.82
 10123.6  179.78 10134.8  180.39 10166.5  180.66 10198.4  183.27 10221.6  184.09
#Mann= 4 ,-1 , 0
  9666.4     .11       0  9987.8    .045       0 10003.6      .1       0
 10077.7     .08       0
Bank Sta=9987.8,10003.6
XS Rating Curve= 0 ,0
Exp/Cntr=0.5,0.3

Type RM Length L Ch R = 1 ,9175.7  ,269.2,299.5,306.7
XS GIS Cut Line= 4
     2003356.315      468079.329     2003319.173      468022.976
     2003142.427      467806.526     2002979.769      467651.553
#Sta/Elev= 30
  9783.1  181.46  9797.1   180.8  9835.3  177.02  9857.1  171.98  9877.6  172.13
    9883  172.02  9898.3  168.88  9928.3  164.97  9937.1  164.39    9986  164.25
  9990.1  162.54  9995.9  161.63  9999.8  161.84 10002.3   162.7 10004.3  164.28
 10032.8  164.19 10075.2  165.18 10095.3   168.5 10126.6  172.27 10148.7  172.91
 10175.6  171.88 10222.6  172.76 10256.2  174.03 10280.3  176.01 10296.4  174.72
 10334.4   175.9 10337.9   177.3 10342.8  178.34 10349.9  181.64 10354.7   183.2
#Mann= 4 ,-1 , 0
  9783.1      .1       0  9877.6     .11       0    9986    .045       0
 10004.3     .12       0
Bank Sta=9986,10004.3
XS Rating Curve= 0 ,0
Exp/Cntr=0.3,0.1

Type RM Length L Ch R = 1 ,8876.2  ,276.9,300.2,357
XS GIS Cut Line= 3
     2003574.615      468031.604     2003392.827      467559.147
     2003339.497      467528.538
#Sta/Elev= 30
  9809.2  180.49  9837.6  178.95  9857.6  178.42  9890.9  176.01  9905.2  173.92
  9931.1  171.59  9940.9   169.3  9957.4  168.18  9966.7  166.55  9977.4  165.53
  9985.8  164.34  9989.7  162.41  9996.4  160.11   10000  159.93 10001.9   160.6
 10004.7  162.38 10009.2     163 10041.8   162.1 10065.6  162.74 10162.8  163.27
   10255  166.38 10277.6  168.43 10290.2   172.7 10308.7  176.14   10313  176.13
 10324.4  178.07 10346.7   179.5 10356.4   181.7 10368.3  182.79 10376.8  184.34
#Mann= 3 ,-1 , 0
  9809.2     .11       0  9989.7    .045       0 10004.7     .12       0
#XS Ineff= 2 , 0
       0                   10150       0     175
Permanent Ineff=
       F       F
Bank Sta=9989.7,10004.7
XS Rating Curve= 0 ,0
Exp/Cntr=0.3,0.1

Type RM Length L Ch R = 1 ,8576    ,197.5,205.2,228.8
XS GIS Cut Line= 2
     2003725.983      468032.896     2003885.679      467447.273
#Sta/Elev= 30
  9775.3  176.22  9806.8  174.23  9811.1  173.51  9861.3  167.81  9867.7  167.79
  9886.9  165.94  9897.2  165.69  9908.9  164.25  9989.1  161.03  9993.3  160.17
  9995.6  159.13   10000  158.58 10001.6  158.83 10006.1  161.16 10011.8  160.39
 10077.5  161.16 10126.4  160.54   10193  161.82 10210.5  163.64 10217.3  166.95
   10237  168.98   10248  171.59 10258.8   172.6 10270.3  174.75 10276.4  176.42
   10284  177.12 10295.2  179.94 10356.7  184.04 10376.2     184 10382.3  182.96
#Mann= 4 ,-1 , 0
  9775.3     .07       0  9811.1     .12       0  9989.1    .045       0
 10006.1     .12       0
#XS Ineff= 2 , 0
       0                   10100       0     174
Permanent Ineff=
       F       F
Bank Sta=9989.1,10006.1
XS Rating Curve= 0 ,0
Exp/Cntr=0.3,0.1

Type RM Length L Ch R = 1 ,8370.8  ,92.3,96.2,96.4
XS GIS Cut Line= 4
     2003881.352      468096.612     2003922.865      468007.031
     2004025.555      467768.877     2004108.581      467482.655
#Sta/Elev= 30
  9757.9  178.92  9779.2  177.94  9822.4  174.42  9868.4  168.92  9894.6  164.96
  9899.5  163.65  9927.3  160.76  9988.7  160.46   10000  157.87 10001.7  157.91
 10007.3   160.5 10013.1  163.93 10016.4  166.72 10021.6  167.22 10034.1  167.42
 10052.4  166.41 10073.3  168.58 10096.3  169.36 10127.3  169.06 10163.9  167.03
   10176  168.91 10186.5  169.33 10201.6   167.8 10207.5  166.46 10219.6  166.55
   10240  168.02 10262.9  168.39 10293.4  170.62 10338.4  172.45   10414  173.71
#Mann= 4 ,-1 , 0
  9757.9     .12       0  9988.7    .045       0 10007.3      .1       0
   10240     .08       0
#XS Ineff= 2 , 0
       0                   10088       0     174
Permanent Ineff=
       F       F
Bank Sta=9988.7,10007.3
XS Rating Curve= 0 ,0
Exp/Cntr=0.5,0.3

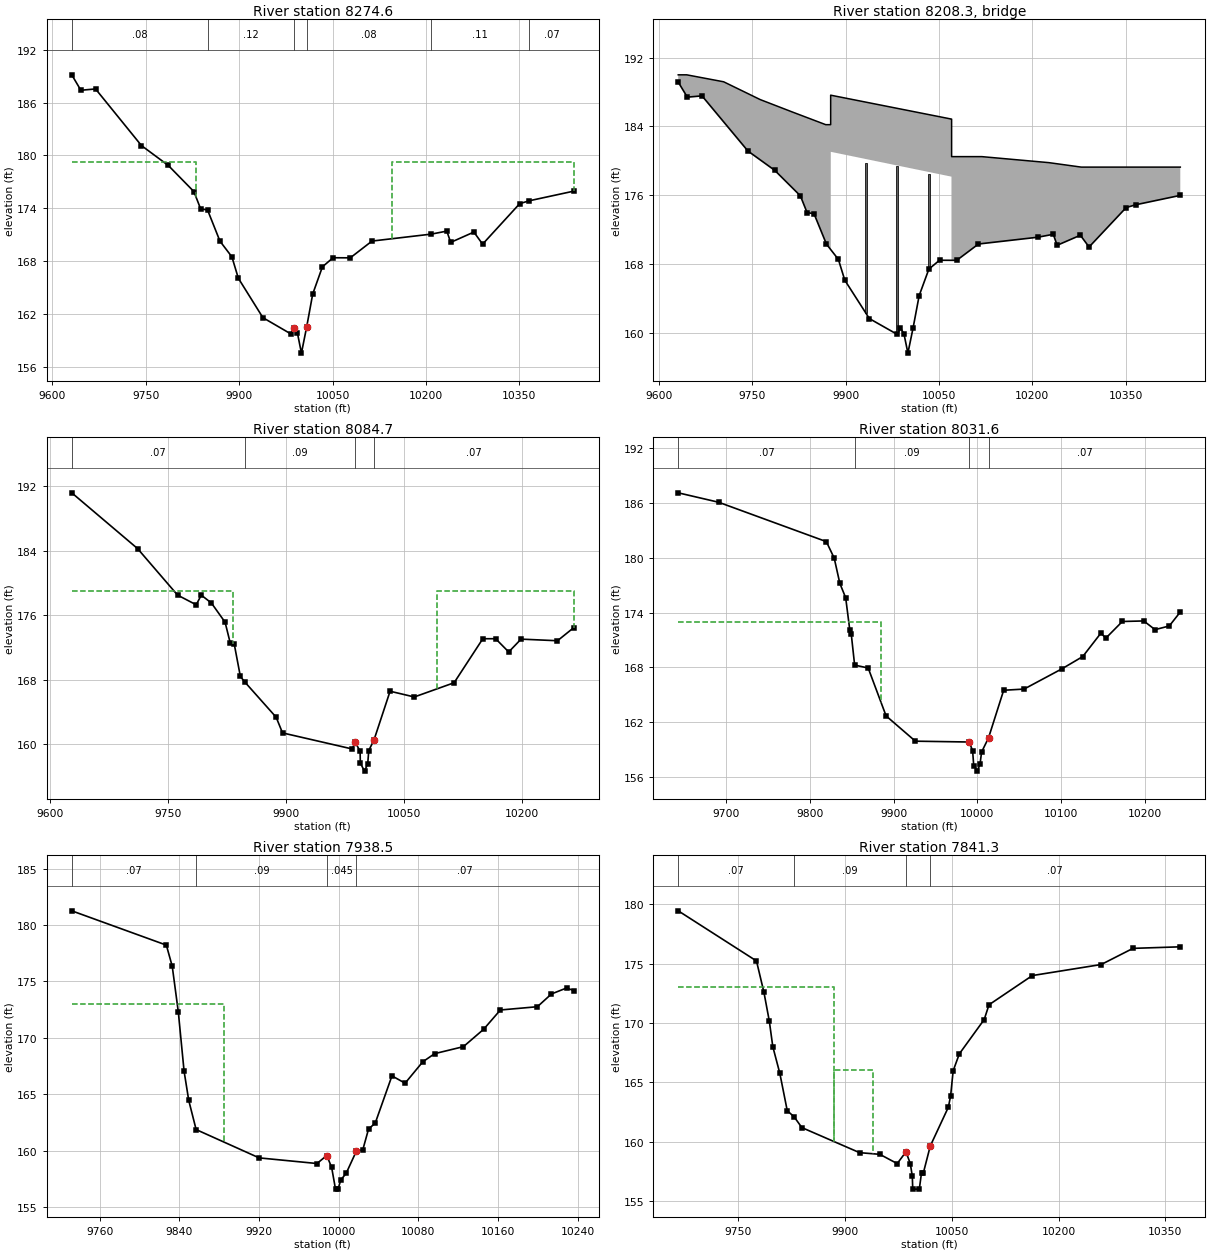
Type RM Length L Ch R = 1 ,8274.6  ,187.1,189.9,190.7
XS GIS Cut Line= 6
     2003878.893      468258.163     2003966.183      468113.865
      2004060.02      467925.171     2004097.652      467841.587
     2004135.672      467741.728     2004210.364      467525.476
#Sta/Elev= 30
    9631  189.14  9645.6  187.39  9669.2  187.54    9743  181.12  9786.1  178.87
  9827.2  175.91    9838  173.96  9849.2  173.82  9869.1  170.29  9888.3  168.51
  9898.6  166.09  9938.1  161.62  9983.2  159.77  9988.1   160.5  9993.6  159.87
   10000   157.6 10008.3  160.52 10018.1  164.29 10033.7  167.38 10050.8  168.41
 10078.5   168.4 10113.4   170.3 10208.9  171.09 10233.6  171.43 10239.8  170.15
 10277.1  171.32 10291.1  169.95 10350.7  174.54 10366.3  174.87 10437.7  175.96
#Mann= 6 ,-1 , 0
    9631     .08       0  9849.2     .12       0  9988.1    .045       0
 10008.3     .08       0 10208.9     .11       0 10366.3     .07       0
#XS Ineff= 2 , 0
       0  9831.1  179.25   10145       0  179.25
Permanent Ineff=
       F       F
Bank Sta=9988.1,10008.3
XS Rating Curve= 0 ,0
Exp/Cntr=0.5,0.3

Type RM Length L Ch R = 3 ,8208.3  ,,,
BEGIN DESCRIPTION:
370076-0011 Bridge: Bunle Road
END DESCRIPTION:
Bridge Culvert-0,0,-1,-1, 0
Deck Dist Width WeirC Skew NumUp NumDn MinLoCord MaxHiCord MaxSubmerge Is_Ogee
45,76.5,2.6,0, 16, 16, 179.25, , 0.95, 0, 0,0,,
    9631  9644.7    9704  9762.7  9814.5    9868  9875.9  9875.9  9876.1   10070
10070.2510070.25 10118.8 10226.5 10278.6 10437.7
  189.99  189.99  189.18  187.11  185.66  184.19  184.19  187.62  187.62  184.84
  184.84  180.47  180.47  179.77  179.25  179.25
                                                                  181.03  178.14
                                                
    9610  9623.7    9683  9741.7  9793.5    9847  9854.9  9854.9  9855.1   10049
10049.2510049.25 10097.8 10205.5 10257.6 10314.6
  189.99  189.99  189.18  187.11  185.66  184.19  184.19  187.62  187.62  184.84
  184.84  180.47  180.47  179.77  179.25  173.92
                                                                  181.03  178.14
                                                
Pier Skew, UpSta & Num, DnSta & Num=  ,9932.8, 4 ,9909.8, 4 , 3 , 3 , 0 ,,
     1.5     1.5    3.25    3.25
  163.37  177.29  177.29  179.72
     1.5     1.5    3.25    3.25
  163.37  177.29  177.29  179.72
Pier Skew, UpSta & Num, DnSta & Num=  ,9982.9, 4 ,9960.2, 4 , 3 , 3 , 0 ,,
     1.5     1.5    3.25    3.25
  160.13  176.41  176.41  179.42
     1.5     1.5    3.25    3.25
  160.13  176.41  176.41  179.42
Pier Skew, UpSta & Num, DnSta & Num=  ,10033.2, 4 ,10009.8, 4 , 3 , 3 , 0 ,,
     1.5     1.5    3.25    3.25
  165.81  175.86  175.86  178.39
     1.5     1.5    3.25    3.25
  165.81  175.86  175.86  178.39
BR Coef= 1 , 1 , 0 ,, 0 ,,,0.8,0,2,0,
WSPro=,,,, 1 ,,,, 0 ,,,, 0 ,,,,-1 ,-1 ,-1 , 0 , 0 , 0 , 0 , 0
BC Design=,, 0 ,, 0 ,,,,,,
BC Use User HTab Curves=0
BC User HTab FreeFlow(D)= 0

Type RM Length L Ch R = 1 ,8084.7  ,83.9,53.1,42.4
XS GIS Cut Line= 6
     2004056.498      468313.384     2004144.756      468167.452
     2004195.675      468066.961     2004239.708      467976.524
     2004278.074      467891.311     2004334.495      467740.564
#Sta/Elev= 30
  9627.9  191.14  9711.5  184.24  9762.4  178.48  9786.1  177.28  9792.5  178.48
  9805.4   177.5  9822.8  175.12  9829.3  172.56  9834.5  172.38  9842.2  168.41
  9847.6  167.75  9887.7  163.36  9895.8  161.42  9984.5  159.43    9988  160.31
  9994.4  159.15  9994.7  157.69   10000  156.69 10004.1   157.6 10005.4  159.24
   10012  160.53 10032.5  166.58 10063.3  165.87 10113.9  167.63 10150.4  173.08
 10166.7  173.08 10183.3  171.44   10199  173.03 10245.3  172.83 10266.1  174.46
#Mann= 4 ,-1 , 0
  9627.9     .07       0  9847.6     .09       0    9988    .045       0
   10012     .07       0
#XS Ineff= 2 , 0
       0  9832.6     179 10092.5       0     179
Permanent Ineff=
       F       F
Bank Sta=9988,10012
XS Rating Curve= 0 ,0
Exp/Cntr=0.5,0.3

Type RM Length L Ch R = 1 ,8031.6  ,100.3,93.1,90.2
XS GIS Cut Line= 4
      2004245.92      468331.698     2004306.411      468119.538
     2004279.841      467933.124     2004345.824      467753.376
#Sta/Elev= 30
  9642.5  187.07  9690.8  186.04  9819.5  181.74  9828.9  179.94  9835.6  177.19
  9842.6  175.61  9847.5   172.1  9849.2   171.7  9853.3  168.26  9869.5  167.94
  9890.9  162.71  9925.9  159.95  9990.2  159.86  9994.3  158.91  9995.6  157.29
   10000  156.68 10003.2  157.46   10005  158.76 10013.3  160.31 10031.4  165.51
 10055.8  165.64   10101  167.85 10125.9  169.19 10147.6  171.75 10153.5   171.2
 10173.2  173.02 10198.8  173.08 10212.3  172.13 10229.3  172.53 10242.5  174.06
#Mann= 4 ,-1 , 0
  9642.5     .07       0  9853.3     .09       0  9990.2    .045       0
 10013.3     .07       0
#XS Ineff= 2 , 0
       0    9885     173               0
Permanent Ineff=
       F       F
Bank Sta=9990.2,10013.3
XS Rating Curve= 0 ,0
Exp/Cntr=0.3,0.1

Type RM Length L Ch R = 1 ,7938.5  ,99.8,97.2,93.5
XS GIS Cut Line= 3
     2004453.893      468225.064      2004359.78      467903.782
      2004359.81      467734.305
#Sta/Elev= 30
  9731.9  181.26  9826.9  178.22  9832.8  176.35  9838.9  172.31  9844.7  167.05
  9849.4  164.45  9856.8  161.87  9920.1  159.36  9978.2  158.86    9988  159.57
  9992.9  158.53  9996.8  156.59  9999.5  156.64 10002.1   157.4 10007.5  157.99
 10017.7  159.95 10024.2  160.07   10030  161.92 10036.7  162.44 10053.5  166.63
 10066.7  165.98 10084.5  167.88 10096.4   168.6 10125.3  169.22 10145.6  170.76
 10162.4  172.47 10199.6  172.76 10213.7  173.89 10228.9  174.42 10236.2  174.19
#Mann= 4 ,-1 , 0
  9731.9     .07       0  9856.8     .09       0    9988    .045       0
 10017.7     .07       0
#XS Ineff= 2 , 0
       0    9885     173               0
Permanent Ineff=
       F       F
Bank Sta=9988,10017.7
XS Rating Curve= 0 ,0
Exp/Cntr=0.5,0.3

Type RM Length L Ch R = 1 ,7841.3  ,216,155.2,151.9
XS GIS Cut Line= 6
     2004588.906      468216.548     2004566.417        468157.8
     2004359.202      467685.651     2004329.494       467642.57
     2004295.275      467606.842        2004276.      467592.081
#Sta/Elev= 30
  9666.3  179.45  9776.1  175.23  9786.6  172.58  9794.1  170.17    9799  168.02
  9808.9  165.76  9819.3  162.62  9828.9  162.11  9839.8   161.2  9920.8  159.09
  9949.2  158.95  9973.6  158.17  9985.9  159.16    9992  158.16  9994.8   157.1
  9995.4  156.02 10004.6  156.02 10007.7  157.39 10010.4  157.41   10020  159.65
 10045.4  162.92 10048.6  163.89 10052.1  165.98 10060.8  167.41 10095.7   170.3
 10102.4  171.54 10163.2     174 10259.9  174.93 10304.5  176.29 10370.9  176.42
#Mann= 4 ,-1 , 0
  9666.3     .07       0  9828.9     .09       0  9985.9    .045       0
   10020     .07       0
#XS Ineff= 3 ,-1
  9666.3    9885     173    9885    9940  166.07   10060 10370.9  166.07
Permanent Ineff=
       F       F       F
Bank Sta=9985.9,10020
XS Rating Curve= 0 ,0
Exp/Cntr=0.5,0.3

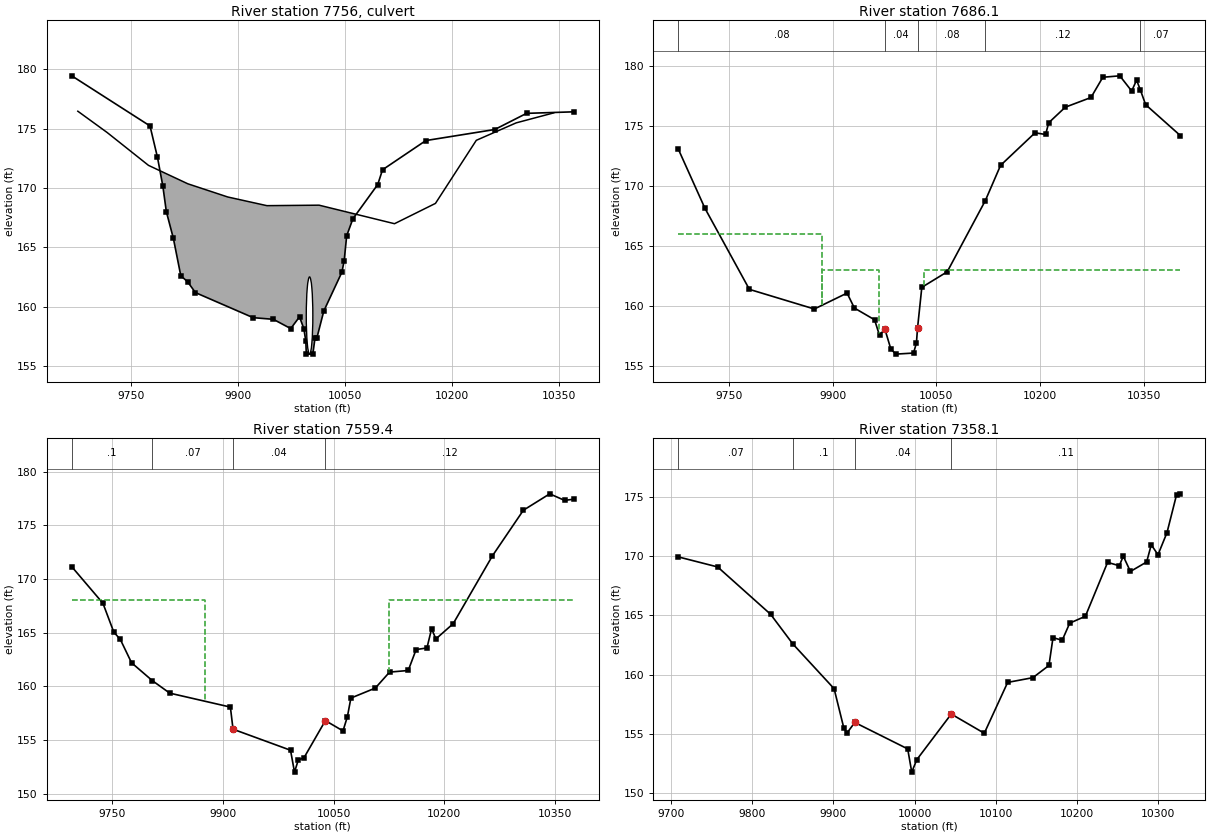
Type RM Length L Ch R = 2 ,7756    ,,,
BEGIN DESCRIPTION:
370076-0012 Culvert: Bingham Drive (Corrugated Metal Elliptical Culvert)
END DESCRIPTION:
Bridge Culvert--1,0,-1,-1, 0
Deck Dist Width WeirC Skew NumUp NumDn MinLoCord MaxHiCord MaxSubmerge Is_Ogee
56,46,2.6,0, 12, 12, 166.07, , 0.95, 0, 0,0,,
  9674.8  9715.9    9774  9829.2  9885.2  9940.1 10013.4 10119.2 10176.7   10234
   10290 10342.6
  176.47  174.68  171.91  170.36  169.25  168.52  168.56     167  168.71  174.02
  175.49  176.33
                                                                                
                
  9674.8  9715.9    9774  9829.2  9885.2  9940.1 10013.4 10119.2 10176.7   10234
   10290 10342.6
  176.47  174.68  171.91  170.36  169.25  168.52  168.56     167  168.71  174.02
  175.49  176.33
                                                                                
                
BR Coef=-1 , 0 , 0 ,, 0 ,,,0.8,-1,,0,
WSPro=,,,, 1 ,,,, 0 ,,,, 0 ,,,,-1 ,-1 ,-1 , 0 , 0 , 0 , 0 , 0
Culvert=4,6.5,9.2,83.3,0.024,0.5,1,29,1,156.02,10000,155.97,10000,Culvert #1  , 0 ,38.8
Culvert Bottom n=0.024
BC Design=,, 0 ,, 0 ,,,,,,
BC Use User HTab Curves=0
BC User HTab FreeFlow(D)= 0

Type RM Length L Ch R = 1 ,7686.1  ,159.7,126.7,116.1
BEGIN DESCRIPTION:
drawdowns exist and could not be removed using standard engineering practice
END DESCRIPTION:
XS GIS Cut Line= 6
     2004722.792      468153.832     2004699.897      468094.023
     2004491.022      467617.951     2004457.132      467568.805
     2004418.565      467528.538      2004396.85      467511.908
#Sta/Elev= 30
  9676.4  173.11    9715  168.16  9779.4  161.38  9873.4  159.74  9920.8  161.07
  9931.4  159.82  9960.6  158.84  9967.8  157.53  9975.4  158.08  9984.2  156.39
  9991.4  155.97   10017  156.06 10021.2   156.9 10022.8  158.14   10029  161.55
 10065.8  162.85 10120.9  168.79   10143  171.74 10192.9  174.46 10208.2  174.32
 10212.7   175.3 10236.7   176.6 10273.9  177.41   10291   179.1 10315.6  179.22
 10332.8  177.95 10339.9  178.86 10345.5  178.02   10353  176.81 10403.2  174.23
#Mann= 5 ,-1 , 0
  9676.4     .08       0  9975.4     .04       0 10022.8     .08       0
 10120.9     .12       0 10345.5     .07       0
#XS Ineff= 3 ,-1
  9676.4    9885     166    9885    9967     163 10032.6 10403.2     163
Permanent Ineff=
       F       F       F
Bank Sta=9975.4,10022.8
XS Rating Curve= 0 ,0
Exp/Cntr=0.5,0.3

Type RM Length L Ch R = 1 ,7559.4  ,249.7,201.3,166.1
XS GIS Cut Line= 4
     2004899.078      468033.652     2004804.032      467914.846
      2004581.39        467664.1     2004497.955      467489.283
#Sta/Elev= 30
  9694.8  171.14  9737.1  167.73  9751.8  165.05  9760.7  164.36  9775.9  162.19
    9804  160.53  9827.7  159.36    9910  158.06  9913.6     156  9991.6  154.04
    9997     152 10002.2  153.15 10009.7  153.32 10038.9   156.8 10062.8  155.84
 10068.8  157.18 10073.5   158.9 10106.6  159.83   10126  161.32 10151.3  161.47
   10162  163.42 10176.7  163.57   10183  165.36 10188.8  164.41 10212.3  165.83
 10265.6  172.16 10307.5   176.4 10343.3  177.93 10363.4  177.32   10376  177.43
#Mann= 4 ,-1 , 0
  9694.8      .1       0    9804     .07       0  9913.6     .04       0
 10038.9     .12       0
#XS Ineff= 2 , 0
       0    9875     168   10125       0     168
Permanent Ineff=
       F       F
Bank Sta=9913.6,10038.9
XS Rating Curve= 0 ,0
Exp/Cntr=0.3,0.1

Type RM Length L Ch R = 1 ,7358.1  ,252.2,213.6,199.3
XS GIS Cut Line= 4
     2005093.498      467733.673     2004995.051      467707.133
     2004615.666      467565.245     2004530.342      467493.043
#Sta/Elev= 30
  9708.7  169.93  9757.3  169.08  9822.5  165.09    9850  162.58  9900.8  158.81
  9912.9  155.46  9916.9  155.09  9926.3  155.96  9991.5  153.73  9996.5  151.77
 10002.7  152.82 10045.2  156.67 10085.9  155.05 10114.7  159.34 10145.8  159.74
 10165.6  160.77 10170.6  163.12 10181.9  162.89 10191.2  164.34 10210.5  164.92
 10237.9  169.47 10252.3  169.18 10257.2  169.99   10266   168.7   10286   169.5
 10291.7  170.95   10300  170.11 10311.1  171.98 10322.9  175.18 10327.5  175.25
#Mann= 4 ,-1 , 0
  9708.7     .07       0    9850      .1       0  9926.3     .04       0
 10045.2     .11       0
Bank Sta=9926.3,10045.2
XS Rating Curve= 0 ,0
Exp/Cntr=0.3,0.1