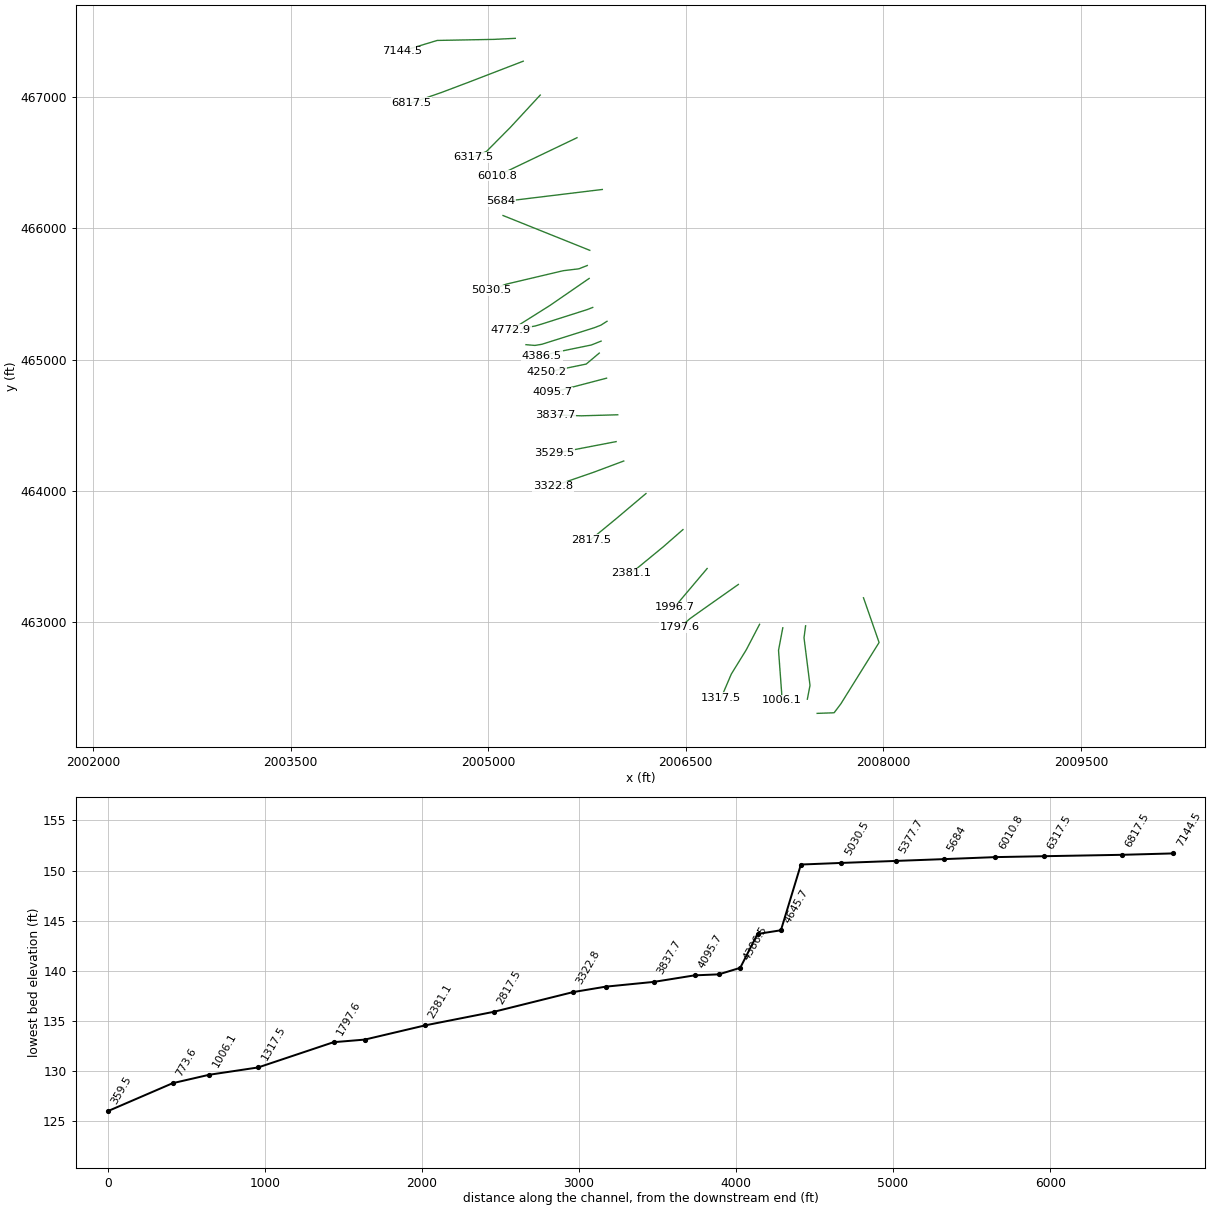
HEC-RAS study BeaverCTA.PRJ: BeaverCTA

--- BeaverCTA.G01 (geometry) --- (continued)

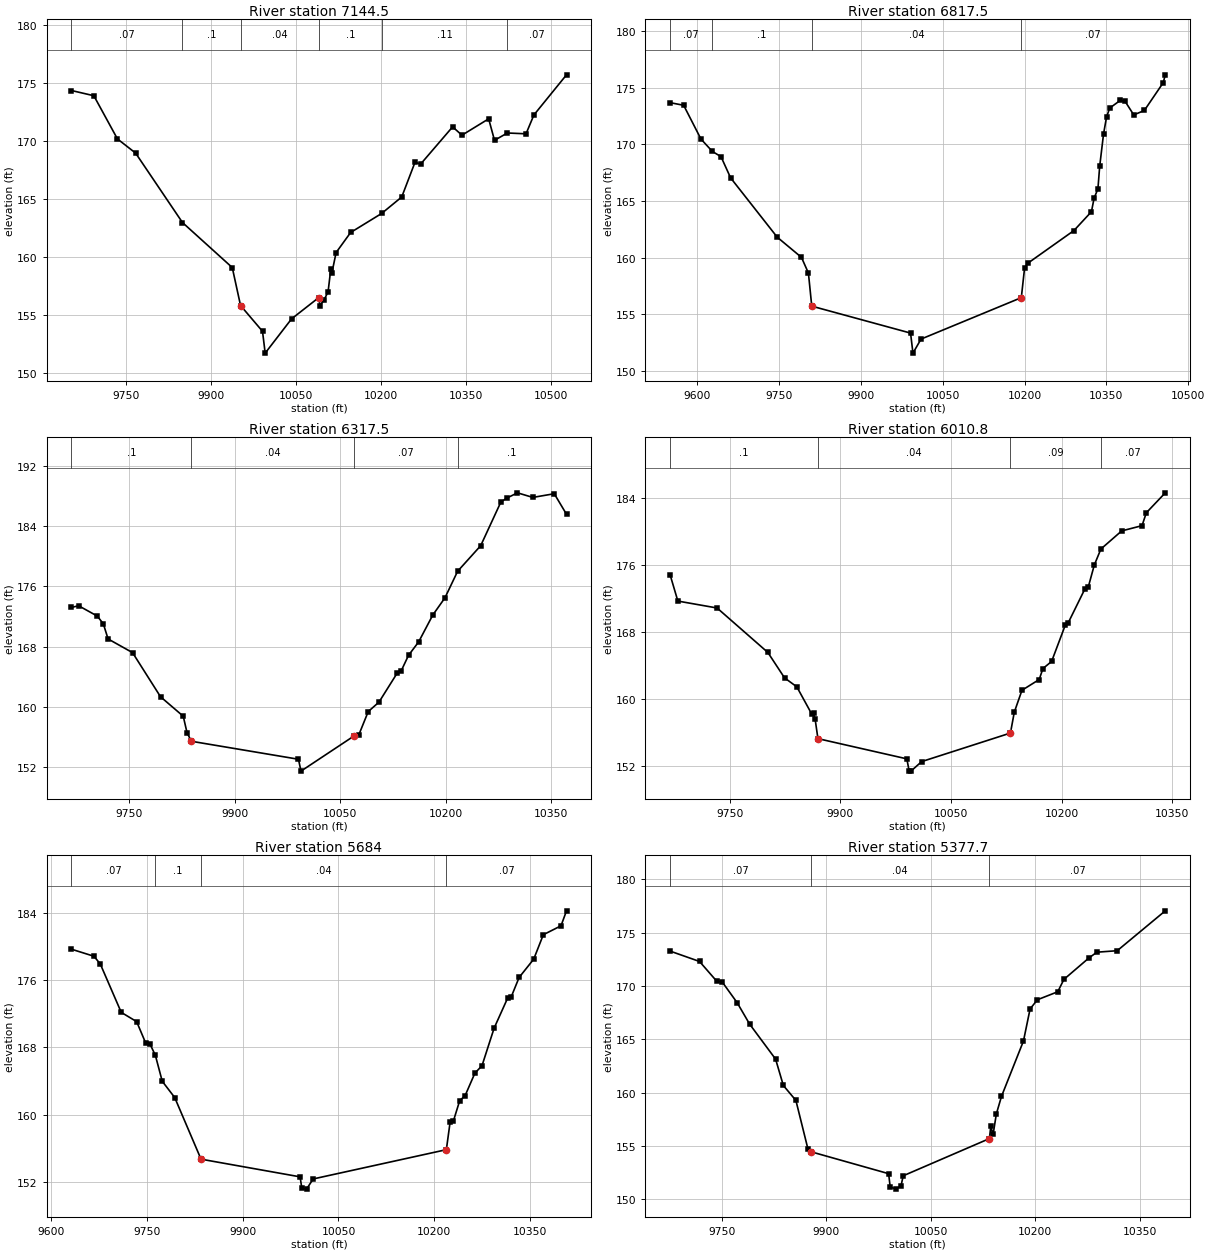
Type RM Length L Ch R = 1 ,7144.5  ,295.1,327,400.3
BEGIN DESCRIPTION:
drawdowns exist and could not be removed using standard engineering practice
END DESCRIPTION:
XS GIS Cut Line= 4
     2005205.758      467443.671     2005042.973       467435.74
     2004612.712      467427.622     2004345.505      467346.235
#Sta/Elev= 30
  9654.5  174.33    9694  173.88  9735.6  170.16  9767.6  168.94  9850.2  162.96
    9938  159.08  9952.6  155.81  9991.3  153.59    9996  151.71 10042.5  154.66
 10090.6   156.5 10092.6  155.79   10100  156.31 10106.9     157 10111.6  158.93
 10113.4  158.57   10121  160.37 10146.6   162.1 10201.3  163.74 10236.7  165.16
 10260.1  168.15   10270  167.99 10326.4   171.2 10342.8  170.48 10389.9  171.89
 10400.2  170.04 10422.9  170.67 10455.8   170.6 10469.6  172.22 10527.1  175.68
#Mann= 6 ,-1 , 0
  9654.5     .07       0  9850.2      .1       0  9952.6     .04       0
 10090.6      .1       0 10201.3     .11       0 10422.9     .07       0
Bank Sta=9952.6,10090.6
XS Rating Curve= 0 ,0
Exp/Cntr=0.3,0.1

Type RM Length L Ch R = 1 ,6817.5  ,395.3,500,611.1
XS GIS Cut Line= 4
     2005266.041       467269.75     2004846.229       467107.69
     2004645.187      467031.721     2004415.826      466951.653
#Sta/Elev= 30
    9550  173.69  9574.7  173.46  9606.4  170.48  9627.2  169.39  9643.2  168.92
  9660.8  167.05  9746.3  161.81  9790.7  160.03  9803.5  158.64  9809.6  155.72
  9990.8  153.34  9995.2  151.57   10010  152.81 10193.9  156.47   10200  159.13
   10207  159.55 10290.5   162.4 10322.5  164.06 10327.4  165.26 10334.4  166.08
 10337.6  168.06 10344.7  170.93 10350.2  172.42 10355.9  173.21 10375.3  173.89
 10384.3   173.8 10400.1  172.61 10419.5     173 10454.2  175.46 10457.9  176.15
#Mann= 4 ,-1 , 0
    9550     .07       0  9627.2      .1       0  9809.6     .04       0
 10193.9     .07       0
Bank Sta=9809.6,10193.9
XS Rating Curve= 0 ,0
Exp/Cntr=0.3,0.1

Type RM Length L Ch R = 1 ,6317.5  ,361.6,306.7,277.3
XS GIS Cut Line= 4
     2005395.219      467012.144      2005169.84      466767.827
      2004987.31      466583.263     2004884.092      466539.958
#Sta/Elev= 30
  9667.6   173.2  9677.9  173.42  9704.4  172.05    9713  171.01  9719.7  169.01
  9754.5  167.19  9794.3  161.32  9826.6  158.73    9832  156.53  9838.2   155.4
  9990.4  153.01    9994  151.43 10069.3   156.1   10076   156.2 10089.6  159.35
 10104.9  160.61   10131   164.5 10136.6  164.79 10146.9  166.83 10161.3  168.62
 10181.4  172.19 10198.7  174.48 10216.7  178.01 10249.5  181.41 10278.1   187.2
 10286.2  187.72 10301.8  188.44 10323.6  187.83 10354.1  188.32 10371.5  185.59
#Mann= 4 ,-1 , 0
  9667.6      .1       0  9838.2     .04       0 10069.3     .07       0
 10216.7      .1       0
Bank Sta=9838.2,10069.3
XS Rating Curve= 0 ,0
Exp/Cntr=0.3,0.1

Type RM Length L Ch R = 1 ,6010.8  ,453.2,326.8,236.6
XS GIS Cut Line= 2
     2005674.195      466687.474     2005068.948      466397.425
#Sta/Elev= 30
  9669.3  174.81  9679.7   171.7  9732.9  170.87  9801.7  165.55  9824.3  162.51
    9841  161.43  9861.1  158.19  9863.6  158.24  9865.7  157.62  9869.6  155.23
  9990.1  152.81  9993.3  151.35  9995.7  151.34 10010.2  152.48 10130.6   155.9
 10135.8  158.39 10146.2  161.02 10169.6  162.31 10174.6  163.62 10186.4  164.47
 10205.2  168.88 10208.5  169.02 10231.4  173.13 10236.2  173.41 10244.3  176.02
 10253.2  177.93 10281.4   180.1   10309  180.73 10314.8  182.27 10340.5  184.66
#Mann= 4 ,-1 , 0
  9669.3      .1       0  9869.6     .04       0 10130.6     .09       0
 10253.2     .07       0
Bank Sta=9869.6,10130.6
XS Rating Curve= 0 ,0
Exp/Cntr=0.3,0.1

Type RM Length L Ch R = 1 ,5684    ,377.4,306.3,258
XS GIS Cut Line= 3
     2005866.541      466293.814     2005211.056      466213.876
      2005096.86      466202.457
#Sta/Elev= 30
  9631.9  179.66  9667.2  178.82  9677.1   177.9  9709.9  172.15    9734  171.05
  9748.2   168.5  9755.2  168.34  9763.3  167.05  9774.1  163.96  9793.6  162.03
  9834.8   154.7  9989.9   152.6  9992.6  151.26   10000  151.14 10010.4  152.35
 10218.9  155.83 10224.8  159.12 10229.7  159.18 10239.8  161.66 10248.2  162.24
 10263.6  164.93 10274.7  165.81 10293.7  170.28 10314.8  173.84 10320.5     174
 10332.8   176.3 10355.7  178.48 10370.7  181.38 10398.4  182.44   10407  184.22
#Mann= 4 ,-1 , 0
  9631.9     .07       0  9763.3      .1       0  9834.8     .04       0
 10218.9     .07       0
Bank Sta=9834.8,10218.9
XS Rating Curve= 0 ,0
Exp/Cntr=0.3,0.1

Type RM Length L Ch R = 1 ,5377.7  ,271.6,347.2,546.7
XS GIS Cut Line= 2
     2005771.437      465830.739     2005112.539       466095.64
#Sta/Elev= 30
  9676.3  173.28  9718.4  172.31  9743.3  170.44  9750.8   170.4  9772.4  168.44
  9790.2  166.44  9827.5  163.15  9838.6  160.68  9856.6  159.28  9873.7  154.77
  9877.9  154.47  9989.6  152.41  9991.8  151.18   10000  150.96 10007.4  151.27
 10010.5  152.21 10134.2   155.7 10136.1  156.84 10139.5   156.1 10144.1  158.01
 10151.5  159.66   10183  164.85 10192.5  167.86   10203  168.72 10232.2  169.47
   10241  170.63 10276.9  172.64 10288.3  173.18 10317.5  173.32 10386.4  177.06
#Mann= 3 ,-1 , 0
  9676.3     .07       0  9877.9     .04       0 10134.2     .07       0
Bank Sta=9877.9,10134.2
XS Rating Curve= 0 ,0
Exp/Cntr=0.3,0.1

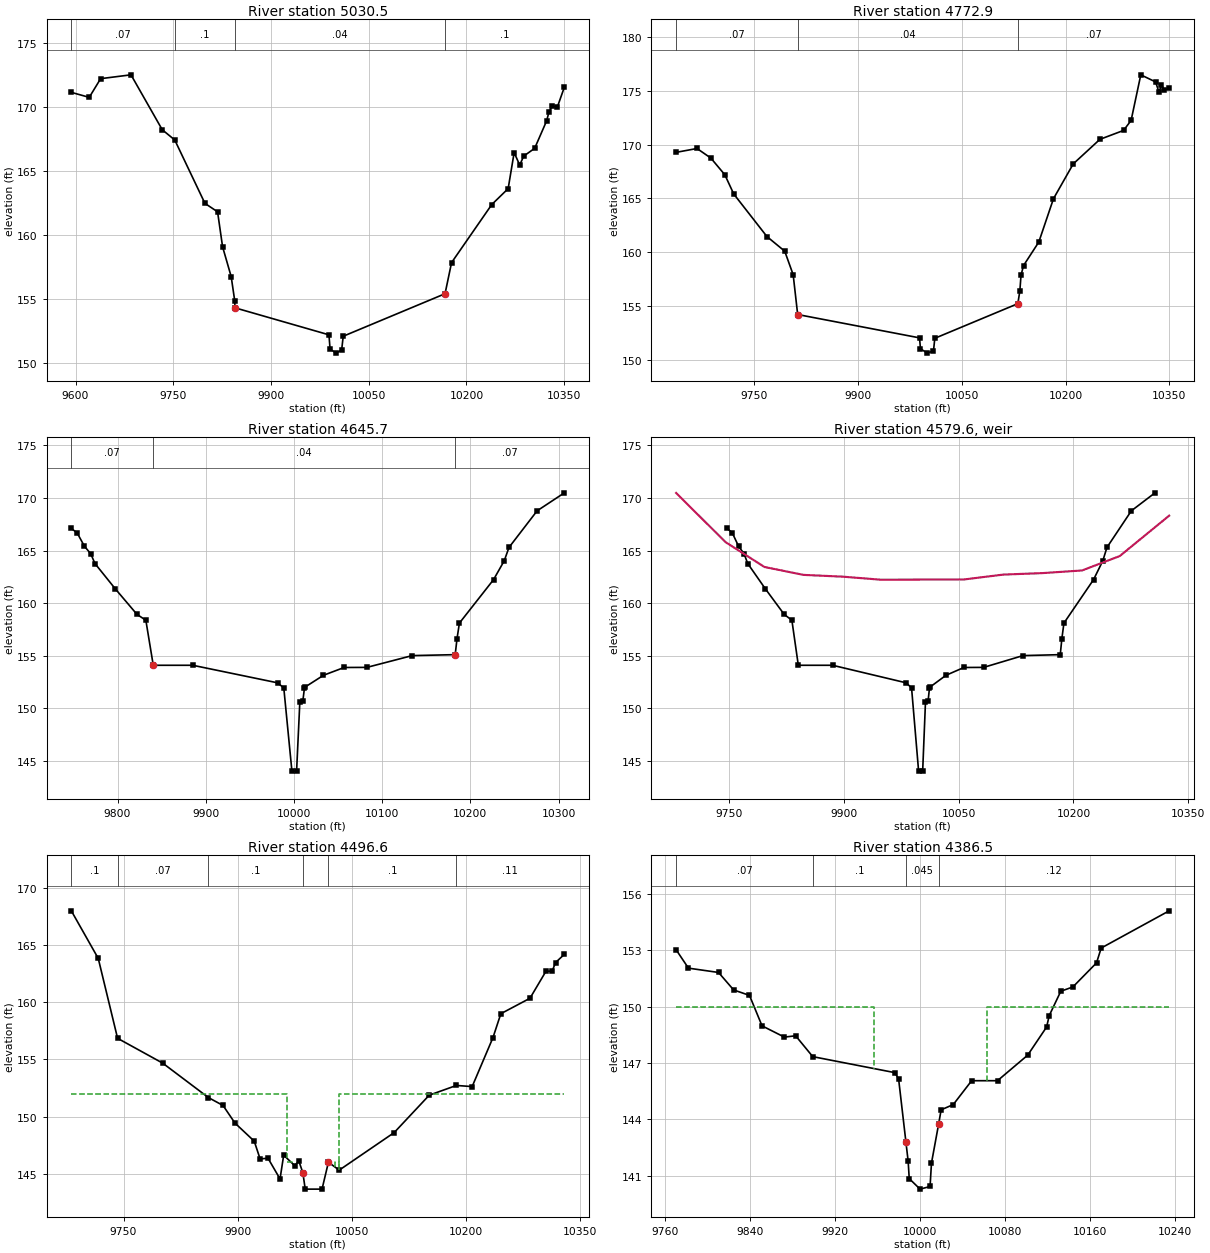
Type RM Length L Ch R = 1 ,5030.5  ,190.2,257.6,316.2
XS GIS Cut Line= 5
     2005752.201        465715.2     2005688.471      465690.138
     2005569.511      465675.695     2005135.867      465573.098
     2005021.791      465527.172
#Sta/Elev= 30
  9593.5  171.13    9621  170.74  9638.5   172.2  9685.1   172.5  9733.1  168.21
  9752.3  167.41  9798.6  162.46    9818   161.8  9825.7  159.07  9838.9  156.74
  9844.4  154.83  9844.7   154.3    9989  152.19  9990.7  151.08   10000  150.76
 10008.5  151.01 10010.9  152.08 10167.2   155.4 10177.2  157.83   10239  162.37
 10264.1  163.61 10273.3  166.43 10281.8  165.45   10288  166.15 10304.8  166.76
 10323.2  168.91 10326.6  169.58 10331.6  170.06 10339.6  169.98 10350.4  171.54
#Mann= 4 ,-1 , 0
  9593.5     .07       0  9752.3      .1       0  9844.7     .04       0
 10167.2      .1       0
Bank Sta=9844.7,10167.2
XS Rating Curve= 0 ,0
Exp/Cntr=0.3,0.1

Type RM Length L Ch R = 1 ,4772.9  ,174.4,127.2,82.7
XS GIS Cut Line= 3
     2005766.603      465616.883     2005467.901      465410.692
     2005172.199      465224.192
#Sta/Elev= 30
    9637  169.27  9667.2  169.63  9687.2  168.74  9707.4  167.19  9720.3   165.4
  9768.3  161.44    9794  160.08  9806.2  157.89  9812.7  154.19  9988.8  152.02
  9990.2  151.01   10000   150.6   10009  150.81 10010.9  151.98 10130.9   155.2
 10133.8  156.38 10135.5  157.84 10139.1  158.74 10161.2  160.93 10182.4  164.96
   10211   168.2 10249.5  170.48 10283.7  171.31 10294.6  172.24 10308.6  176.48
   10330  175.82 10334.9  174.87 10338.5  175.56 10342.6  175.03 10349.6  175.26
#Mann= 3 ,-1 , 0
    9637     .07       0  9812.7     .04       0 10130.9     .07       0
Bank Sta=9812.7,10130.9
XS Rating Curve= 0 ,0
Exp/Cntr=0.5,0.3

Type RM Length L Ch R = 1 ,4645.7  ,255,149.1,276.7
XS GIS Cut Line= 6
     2005793.729      465396.247      2005749.57      465379.081
     2005404.153      465269.084     2005356.202      465254.769
     2005311.202      465247.289     2005259.396       465234.14
#Sta/Elev= 30
  9747.6  167.11  9754.3  166.67  9762.4  165.42  9769.6   164.7  9774.4  163.77
  9797.3  161.38    9822  158.94  9832.1  158.38  9840.5   154.1  9885.3   154.1
  9981.6  152.43  9988.5  151.94  9997.7  144.04   10003  144.04 10006.7  150.65
 10010.1  150.72 10011.9  151.93   10013  152.05 10033.5  153.15 10056.9  153.89
 10082.7   153.9 10134.1  155.02 10182.8  155.11 10184.9  156.64 10187.6  158.11
 10226.3  162.24 10238.4  164.03 10243.8   165.3 10275.7  168.78 10306.6  170.49
#Mann= 3 ,-1 , 0
  9747.6     .07       0  9840.5     .04       0 10182.8     .07       0
Bank Sta=9840.5,10182.8
XS Rating Curve= 0 ,0
Exp/Cntr=0.5,0.3

Type RM Length L Ch R = 5 ,4579.6  ,,,
BEGIN DESCRIPTION:
370076-0013 Culvert: Greenock Avenue
END DESCRIPTION:
IW Pilot Flow=0
#Inline Weir SE= 12
  9680.8  170.48  9745.5   165.8  9796.3  163.44  9847.5  162.69    9899  162.52
  9948.8  162.23 10057.5  162.26 10108.5  162.72 10159.6  162.86 10211.2  163.11
 10260.5  164.48 10325.1  168.32
IW Dist,WD,Coef,Skew,MaxSub,Min_El,Is_Ogee,SpillHt,DesHd
56,24,2.6,0,0.98,, 0 ,,,0,0,

Type RM Length L Ch R = 1 ,4496.6  ,112,110.1,98.5
XS GIS Cut Line= 6
     2005902.207      465291.011     2005855.508      465261.265
     2005804.909      465241.595     2005407.129      465115.925
     2005354.734      465107.215     2005286.897       465112.88
#Sta/Elev= 30
  9681.4  167.99  9716.8  163.83  9742.2  156.85  9801.5  154.68  9861.6  151.67
  9880.8  150.98  9896.5  149.44  9921.8  147.86  9929.5  146.31  9939.9  146.37
  9955.7  144.56  9960.5  146.64    9975  145.72  9980.4  146.13  9985.7   145.1
  9988.8  143.67 10010.9  143.67 10019.3  146.02 10033.5  145.33 10105.7  148.61
 10151.8  151.88 10187.5  152.73 10208.2  152.63 10235.6  156.92 10245.9     159
 10284.2  160.35 10305.2  162.71 10313.3  162.71 10317.8  163.47 10329.4  164.19
#Mann= 6 ,-1 , 0
  9681.4      .1       0  9742.2     .07       0  9861.6      .1       0
  9985.7    .045       0 10019.3      .1       0 10187.5     .11       0
#XS Ineff= 4 ,-1
  9681.4    9965     152    9965    9972     146   10028   10033     146
   10033 10329.4     152
Permanent Ineff=
       F       F       F       F
Bank Sta=9985.7,10019.3
XS Rating Curve= 0 ,0
Exp/Cntr=0.5,0.3

Type RM Length L Ch R = 1 ,4386.5  ,136.3,136.3,135.3
XS GIS Cut Line= 4
     2005857.043      465139.999     2005783.581      465110.614
     2005500.552      465052.484     2005408.457      465026.902
#Sta/Elev= 30
  9770.6  153.03  9782.2  152.05  9810.5  151.82  9824.7  150.89  9839.6   150.6
  9851.4  148.98  9872.4  148.38    9883  148.45  9899.1  147.34  9976.2  146.49
  9979.8  146.16  9986.7  142.79  9988.8  141.77  9989.8  140.85   10000  140.29
 10009.4  140.43 10010.7  141.67 10017.5  143.77 10019.8  144.51 10031.2  144.79
 10048.5  146.06 10072.8  146.06 10101.2  147.42   10119  148.92 10121.4  149.52
 10132.3  150.82 10143.7  151.05 10165.9  152.33 10170.3  153.12 10234.2   155.1
#Mann= 4 ,-1 , 0
  9770.6     .07       0  9899.1      .1       0  9986.7    .045       0
 10017.5     .12       0
#XS Ineff= 2 , 0
       0    9957     150   10063       0     150
Permanent Ineff=
       F       F
Bank Sta=9986.7,10017.5
XS Rating Curve= 0 ,0
Exp/Cntr=0.3,0.1

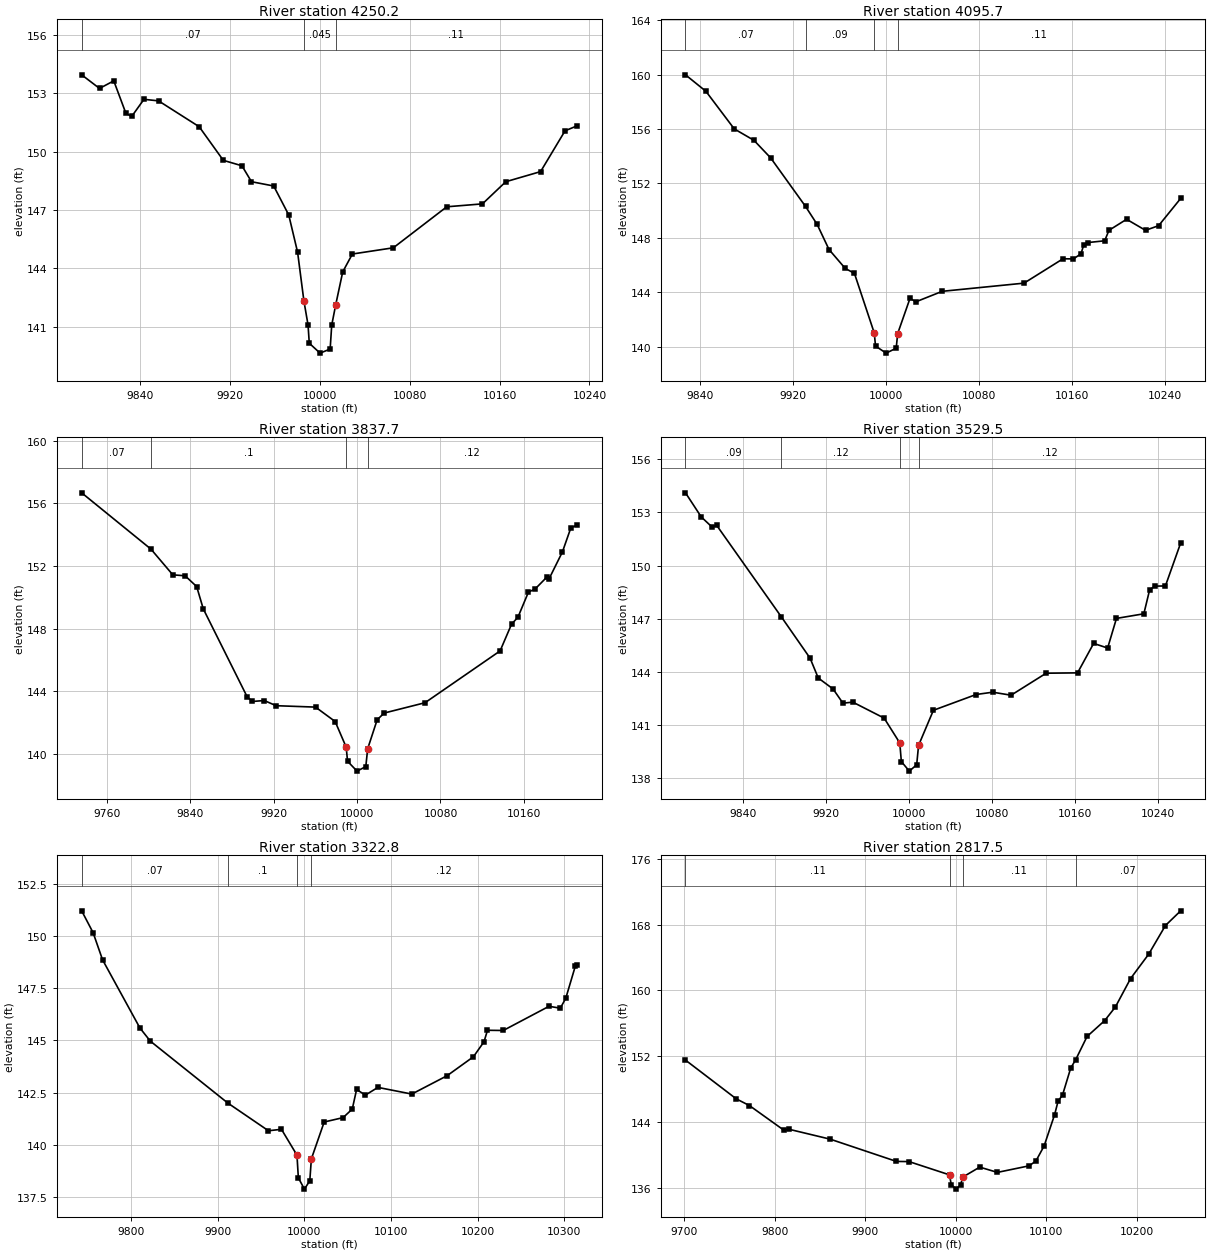
Type RM Length L Ch R = 1 ,4250.2  ,153.1,154.5,149.7
XS GIS Cut Line= 3
     2005843.348      465049.073     2005744.432      464965.506
     2005439.156      464902.404
#Sta/Elev= 30
  9787.6  153.96  9803.5  153.26  9816.2  153.65    9827  151.98  9832.2  151.82
  9843.1   152.7  9856.1  152.62  9892.3  151.29  9913.8  149.56  9930.4  149.28
  9938.9  148.46  9958.7  148.24  9972.1  146.75    9980  144.83  9985.6  142.33
  9989.3  141.09  9990.4  140.15   10000  139.64   10009  139.85 10010.4  141.08
   10014  142.14 10020.2  143.82 10028.8  144.74 10065.3  145.06 10112.9  147.17
 10144.7  147.32 10165.5  148.46 10196.5  148.98 10218.3  151.08 10228.8  151.33
#Mann= 3 ,-1 , 0
  9787.6     .07       0  9985.6    .045       0   10014     .11       0
Bank Sta=9985.6,10014
XS Rating Curve= 0 ,0
Exp/Cntr=0.3,0.1

Type RM Length L Ch R = 1 ,4095.7  ,251.3,258,224.8
XS GIS Cut Line= 2
     2005898.778       464858.11     2005486.003      464749.757
#Sta/Elev= 30
  9827.1  159.98  9844.7  158.77  9869.1  156.01  9886.1  155.17  9900.5  153.88
  9930.6  150.31  9940.6  148.99  9950.8  147.15  9964.8  145.76  9972.7   145.4
  9989.8  141.02  9990.9  140.06   10000  139.54 10008.7   139.9   10010  140.98
 10020.6  143.56 10025.7  143.31 10048.4  144.08 10118.9  144.68 10152.5  146.47
 10161.5  146.46   10168  146.84 10170.4   147.5 10173.8  147.66 10188.4  147.79
 10192.1  148.56 10207.3  149.37 10223.6  148.56 10234.9   148.9 10253.9   150.9
#Mann= 4 ,-1 , 0
  9827.1     .07       0  9930.6     .09       0  9989.8    .045       0
   10010     .11       0
Bank Sta=9989.8,10010
XS Rating Curve= 0 ,0
Exp/Cntr=0.3,0.1

Type RM Length L Ch R = 1 ,3837.7  ,231.2,308.2,258.3
XS GIS Cut Line= 3
     2005983.912      464579.487      2005706.58      464571.748
     2005509.222      464578.197
#Sta/Elev= 30
  9735.9  156.67  9802.4  153.07  9823.3  151.43  9835.1  151.37  9846.2  150.68
  9852.5  149.26  9894.6  143.64  9899.6  143.34    9911   143.4  9922.4  143.07
  9960.2  142.98    9979  142.06  9989.6  140.42  9990.9  139.52   10000  138.89
 10008.4  139.18 10010.2  140.32 10019.3  142.17   10026   142.6 10065.2  143.26
 10137.2  146.57 10148.2  148.28 10154.3  148.72 10164.4  150.33 10170.7  150.52
 10182.4  151.31 10184.2  151.18   10197   152.9   10205  154.42 10210.8  154.61
#Mann= 4 ,-1 , 0
  9735.9     .07       0  9802.4      .1       0  9989.6    .045       0
 10010.2     .12       0
Bank Sta=9989.6,10010.2
XS Rating Curve= 0 ,0
Exp/Cntr=0.3,0.1

Type RM Length L Ch R = 1 ,3529.5  ,187.5,206.7,207.6
XS GIS Cut Line= 2
     2005971.393       464375.39     2005502.257       464285.03
#Sta/Elev= 30
  9784.2   154.1  9799.4  152.74    9810  152.16  9814.1  152.28  9876.7   147.1
  9904.3  144.78  9912.2  143.66  9926.5  143.04    9936  142.24  9945.5   142.3
  9975.7   141.4  9990.8     140  9992.3  138.95   10000  138.41 10007.1  138.77
 10008.9  139.86 10023.2  141.84 10064.4  142.73 10080.4  142.86 10098.1  142.69
 10131.9  143.93 10162.2  143.95 10177.7  145.61 10191.2  145.35 10199.7  147.02
 10226.1  147.28 10231.6  148.61 10236.4  148.84 10246.9  148.85 10261.6  151.27
#Mann= 4 ,-1 , 0
  9784.2     .09       0  9876.7     .12       0  9990.8    .045       0
 10008.9     .12       0
Bank Sta=9990.8,10008.9
XS Rating Curve= 0 ,0
Exp/Cntr=0.3,0.1

Type RM Length L Ch R = 1 ,3322.8  ,375.5,505.3,430.9
XS GIS Cut Line= 3
     2006029.234      464227.911     2005798.689      464141.479
     2005491.459       464035.35
#Sta/Elev= 30
    9743  151.22  9756.2  150.17  9767.1  148.87  9810.2   145.6  9822.2  144.97
  9911.6     142  9958.5  140.67  9973.5  140.74  9991.4   139.5    9993  138.41
   10000  137.87 10006.2  138.27   10008  139.32 10022.8  141.09 10044.6   141.3
 10055.2  141.71 10060.2  142.65 10070.3  142.38 10084.8  142.75 10123.9  142.43
 10164.6  143.31   10195  144.22 10207.2  144.94 10211.2  145.49 10229.4  145.48
 10282.2  146.64 10295.2  146.55 10301.5  147.02 10312.5  148.56 10314.3   148.6
#Mann= 4 ,-1 , 0
    9743     .07       0  9911.6      .1       0  9991.4    .045       0
   10008     .12       0
Bank Sta=9991.4,10008
XS Rating Curve= 0 ,0
Exp/Cntr=0.3,0.1

Type RM Length L Ch R = 1 ,2817.5  ,408.1,436.4,404
XS GIS Cut Line= 3
     2006197.998      463980.393     2005969.875      463787.338
     2005778.243      463629.589
#Sta/Elev= 30
  9701.2  151.55  9757.3  146.85  9771.8  146.04  9809.5  143.08    9816  143.15
  9861.1  141.96  9934.3  139.26  9948.2  139.24  9992.9  137.63  9994.8  136.46
   10000   135.9 10005.2   136.4 10007.4  137.35 10026.3  138.57 10045.8  137.93
   10081  138.73 10088.4  139.32 10097.4  141.13   10109  144.92 10112.9  146.58
 10117.8  147.32 10126.8  150.58 10132.4  151.62 10144.9  154.42 10164.4  156.35
 10176.2     158   10193  161.45 10212.9  164.39 10231.5  167.88 10248.3  169.66
#Mann= 4 ,-1 , 0
  9701.2     .11       0  9992.9    .045       0 10007.4     .11       0
 10132.4     .07       0
Bank Sta=9992.9,10007.4
XS Rating Curve= 0 ,0
Exp/Cntr=0.3,0.1

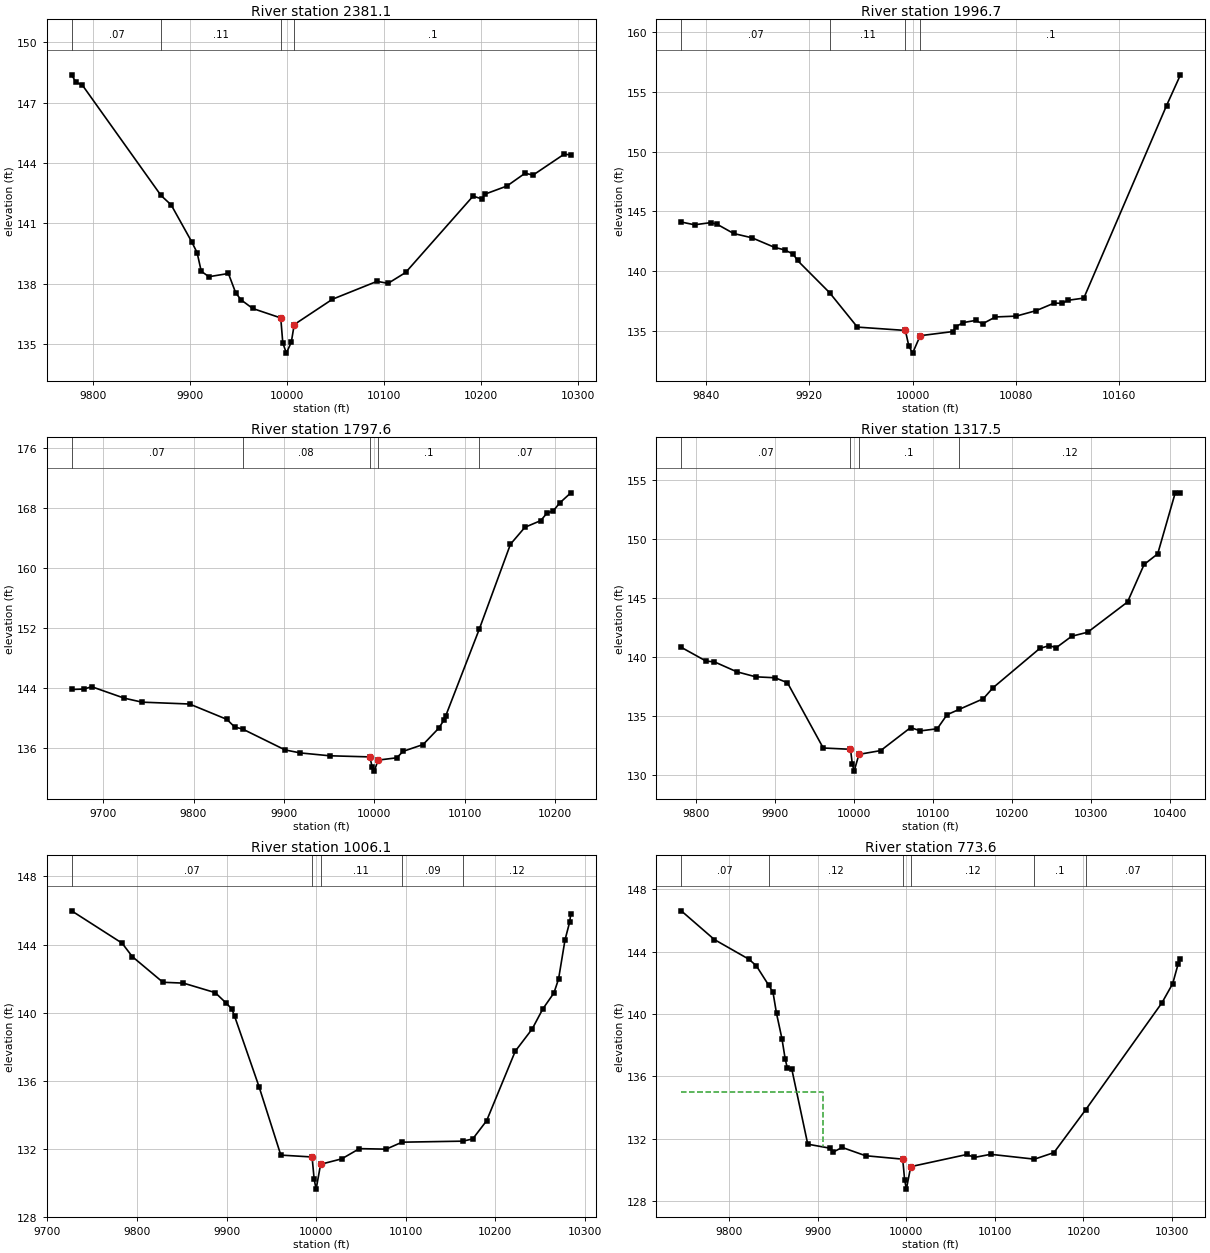
Type RM Length L Ch R = 1 ,2381.1  ,365.4,384.4,385.3
XS GIS Cut Line= 3
     2006479.088      463706.208     2006329.034      463574.859
      2006085.39      463374.437
#Sta/Elev= 30
  9778.2  148.39  9782.8  148.01  9789.1  147.89  9870.4  142.39  9880.9  141.92
  9901.9   140.1  9907.6  139.55  9911.9  138.62  9919.8  138.35  9939.9  138.51
  9947.5  137.54  9953.2  137.19    9965  136.77  9993.9   136.3    9996  135.06
  9999.7  134.55 10004.8   135.1 10007.8  135.97 10047.2  137.23 10093.2  138.12
 10104.6  138.02 10122.7  138.56 10192.3  142.36 10201.8  142.21 10204.2  142.45
 10227.2  142.86   10246   143.5   10254   143.4 10286.4  144.45 10293.1   144.4
#Mann= 4 ,-1 , 0
  9778.2     .07       0  9870.4     .11       0  9993.9    .045       0
 10007.8      .1       0
Bank Sta=9993.9,10007.8
XS Rating Curve= 0 ,0
Exp/Cntr=0.3,0.1

Type RM Length L Ch R = 1 ,1996.7  ,204.3,199.1,177.6
XS GIS Cut Line= 2
     2006662.326       463409.82     2006412.929      463114.061
#Sta/Elev= 30
  9820.7  144.11    9831  143.88  9843.5  144.06  9848.4  143.93  9861.3  143.15
  9875.5  142.79    9893  141.99    9901  141.77  9907.5  141.42  9910.8  140.89
  9935.6   138.2  9957.2  135.31  9994.4  135.03  9997.1  133.72   10000  133.13
 10005.9  134.59 10031.5  134.94 10033.4  135.34 10039.3  135.69 10048.9  135.87
 10054.3  135.59 10064.2  136.16 10080.3  136.23 10095.8  136.69 10109.7  137.32
 10116.1   137.3 10120.1  137.55 10132.7  137.74 10196.8  153.86 10207.6  156.44
#Mann= 4 ,-1 , 0
  9820.7     .07       0  9935.6     .11       0  9994.4    .045       0
 10005.9      .1       0
Bank Sta=9994.4,10005.9
XS Rating Curve= 0 ,0
Exp/Cntr=0.3,0.1

Type RM Length L Ch R = 1 ,1797.6  ,434.5,480.1,485.5
XS GIS Cut Line= 4
     2006899.564       463288.69      2006625.92      463095.538
     2006531.389      463028.124     2006455.294      462961.129
#Sta/Elev= 30
  9665.1  143.77  9678.7  143.83  9687.3  144.14  9723.4  142.61    9743  142.08
  9795.6  141.83  9836.9  139.78  9845.5  138.76  9854.3  138.49  9901.3   135.7
  9918.2   135.3  9950.6  134.92  9995.1  134.77  9997.6  133.45   10000  132.87
 10004.2  134.34 10024.9  134.65 10031.9  135.51   10054  136.42 10071.1  138.57
 10076.9  139.64 10078.9   140.2 10116.2  151.83 10150.7  163.17 10166.7  165.43
 10184.2  166.32 10190.8  167.28 10198.2  167.65 10205.4   168.7 10217.5  170.03
#Mann= 5 ,-1 , 0
  9665.1     .07       0  9854.3     .08       0  9995.1    .045       0
 10004.2      .1       0 10116.2     .07       0
Bank Sta=9995.1,10004.2
XS Rating Curve= 0 ,0
Exp/Cntr=0.3,0.1

Type RM Length L Ch R = 1 ,1317.5  ,254.6,311.4,336
XS GIS Cut Line= 4
     2007060.535      462985.472     2006959.444      462791.169
     2006845.879        462606.9     2006768.882       462426.33
#Sta/Elev= 30
    9781  140.84  9812.5  139.67  9822.9  139.61  9851.2  138.77  9875.3  138.34
  9899.7  138.26  9915.4  137.84  9960.7  132.31  9995.2   132.2  9997.5  130.95
  9999.8  130.35 10005.9  131.77 10033.4  132.09 10071.3  134.04 10083.7  133.76
   10105  133.94 10117.4  135.13   10133  135.59 10163.2  136.48 10175.5  137.41
 10234.8  140.75 10246.6  140.98 10255.6  140.81 10275.2  141.78 10295.4  142.12
 10345.8  144.68 10366.8  147.86   10384  148.76 10406.2  153.93 10412.8  153.89
#Mann= 4 ,-1 , 0
    9781     .07       0  9995.2    .045       0 10005.9      .1       0
   10133     .12       0
Bank Sta=9995.2,10005.9
XS Rating Curve= 0 ,0
Exp/Cntr=0.3,0.1

Type RM Length L Ch R = 1 ,1006.1  ,210,232.5,213.1
XS GIS Cut Line= 4
     2007236.796      462958.997     2007204.441      462787.514
     2007228.326      462462.329     2007228.707      462405.721
#Sta/Elev= 30
  9727.1  145.98  9783.4  144.08  9794.8  143.29    9829  141.78  9851.9  141.73
  9887.4  141.17  9899.9  140.54  9905.9  140.21  9908.9   139.8  9936.3  135.64
  9960.6  131.62  9995.5  131.51  9997.8   130.2   10000  129.62   10005  131.08
 10028.6   131.4 10048.3     132 10078.2  131.97 10095.9  132.38 10163.7  132.44
 10174.8  132.57 10190.3  133.64 10222.3  137.73 10241.1  139.03   10253  140.21
 10265.4  141.15 10270.6  141.97 10277.8  144.27   10283  145.32 10284.3  145.82
#Mann= 5 ,-1 , 0
  9727.1     .07       0  9995.5    .045       0   10005     .11       0
 10095.9     .09       0 10163.7     .12       0
Bank Sta=9995.5,10005
XS Rating Curve= 0 ,0
Exp/Cntr=0.3,0.1

Type RM Length L Ch R = 1 ,773.6   ,458.1,414.1,355.8
XS GIS Cut Line= 4
     2007409.968      462974.124     2007397.929      462882.478
     2007443.407      462520.853     2007423.344      462415.805
#Sta/Elev= 30
  9745.7  146.61  9783.1  144.77  9822.1  143.51  9830.5  143.09  9844.5  141.84
  9849.3   141.4  9853.3  140.04  9859.4  138.43  9863.1  137.12  9865.6  136.52
  9870.6  136.46  9888.6  131.66    9914   131.4  9917.4  131.16  9927.5  131.45
  9953.9  130.92  9995.9   130.7    9998  129.38   10000  128.78 10004.9  130.22
 10068.4     131 10076.8  130.81 10095.2  131.01 10144.7   130.7 10166.7  131.12
 10202.6  133.87 10288.6  140.71 10300.8  141.94   10307  143.21 10309.6  143.54
#Mann= 6 ,-1 , 0
  9745.7     .07       0  9844.5     .12       0  9995.9    .045       0
 10004.9     .12       0 10144.7      .1       0 10202.6     .07       0
#XS Ineff= 2 , 0
       0    9906     135               0
Permanent Ineff=
       F       F
Bank Sta=9995.9,10004.9
XS Rating Curve= 0 ,0
Exp/Cntr=0.3,0.1

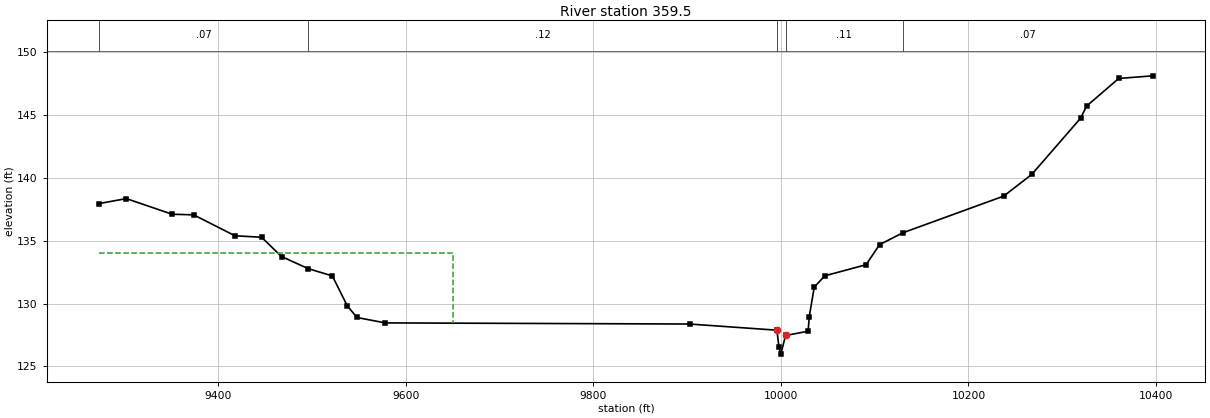
Type RM Length L Ch R = 1 ,359.5   ,366.8,359.5,397.6
XS GIS Cut Line= 5
      2007849.59       463187.21     2007967.987      462847.073
      2007677.64      462380.346     2007626.284       462312.34
     2007497.807      462307.752
#Sta/Elev= 30
  9273.2  137.94    9302  138.33  9350.8  137.09  9373.8  137.04  9417.8  135.38
  9446.2  135.26  9467.5  133.73  9495.9  132.77  9521.7  132.19  9537.5  129.83
  9547.9  128.89  9578.1  128.46  9902.7  128.37  9995.8  127.88  9997.9  126.57
   10000  125.98   10005  127.46 10029.1   127.8 10030.3  128.96 10035.6   131.3
 10046.9   132.2 10090.9  133.08 10105.2  134.67 10129.9  135.61 10237.7  138.53
 10267.7  140.26 10319.6  144.71 10326.1  145.68 10360.3  147.87 10396.6  148.08
#Mann= 5 ,-1 , 0
  9273.2     .07       0  9495.9     .12       0  9995.8    .045       0
   10005     .11       0 10129.9     .07       0
#XS Ineff= 2 , 0
       0    9650     134               0
Permanent Ineff=
       F       F
Bank Sta=9995.8,10005
XS Rating Curve= 0 ,0
Exp/Cntr=0.3,0.1

Chan Stop Cuts=-1
Use User Specified Reach Order=0
Composite Channel Slope=5